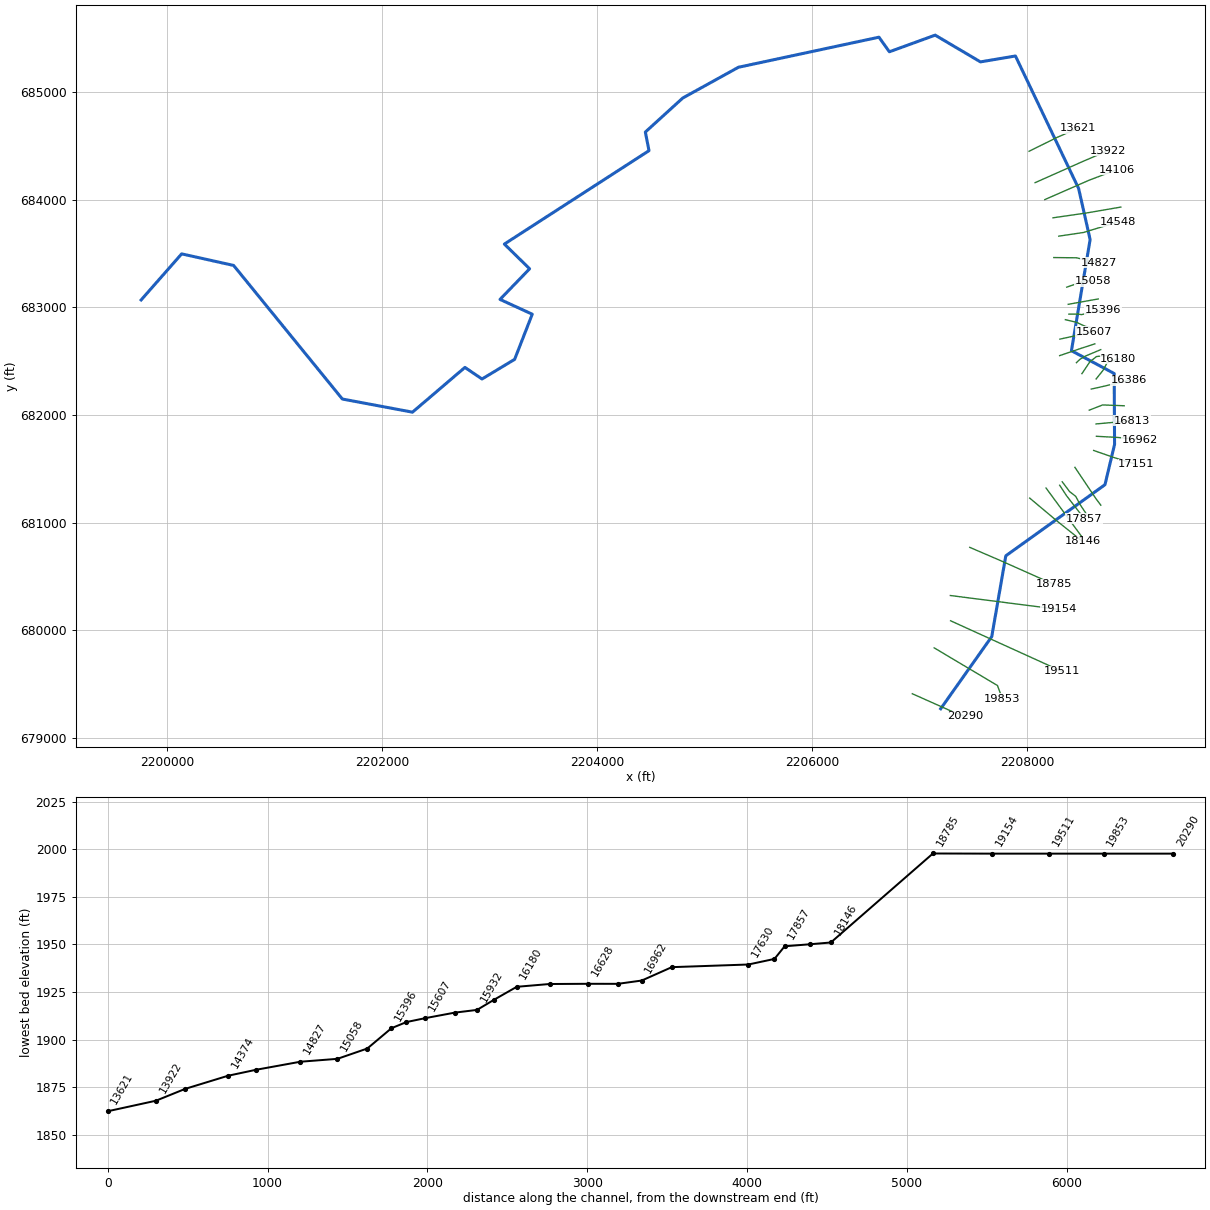
--- TENMILECK.prj (project) ---

Proj Title=TENMILECK
Current Plan=p01
Default Exp/Contr=0,0
English Units
Geom File=g01
Flow File=f01
Plan File=p01
BEGIN DESCRIPTION:
-------- MODELED AS PART OF WVEMD CTP PROGRAM, 2023----------
Stream Name: Tenmile Creek
Flood Zone:  AFH
Upshur County, WV
HEC-RAS Version: RAS 6.3
Vertical Datum: NAVD88
Projection: NAD 1983 StatePlane West Virginia S FIPS 4702 (US Feet)
Terrain: 1-meter LIDAR (FEMA Region III 3DEP collected 2016-2018)
Land Use: 2019 NLCD
Hydrologic Method:
WV SIR2010-5033 regression equations
Additional Model Notes:
None
END DESCRIPTION:
DSS Export Rating Curves= 0
DSS Export Rating Curve Sorted= 0
DSS Export Volume Flow Curves= 0
DXF OffsetX= 0
DXF OffsetY= 0
DXF ScaleX= 0
DXF ScaleY= 0

--- TENMILECK.p01 (plan) ---

Plan Title=Floodplain
Program Version=6.31
Short Identifier=Floodplain
Geom File=g01
Flow File=f01
Subcritical Flow
K Sum by GR= 0
Std Step Tol= 0.01
Critical Tol= 0.01
Num of Std Step Trials= 20
Max Error Tol= 0.3
Flow Tol Ratio= 0.001
Split Flow NTrial= 30
Split Flow Tol= 0.02
Split Flow Ratio= 0.02
Log Output Level= 0
Friction Slope Method= 1
Unsteady Friction Slope Method= 2
Unsteady Bridges Friction Slope Method= 1
Parabolic Critical Depth
Global Vel Dist= 0 , 0 , 0
Global Log Level= 0
CheckData=True
Encroach Param=-1 ,0,0, 0
Mapping Interval=1HOUR
Computation Time Step Use Courant=        0
Computation Time Step Use Time Series=    0
Computation Time Step Count To Double=0
Computation Time Step Max Doubling=0
Computation Time Step Max Halving=0
Computation Time Step Residence Courant=0
Run HTab= 0
Run UNet= 0
Run Sediment= 0
Run PostProcess= 0
Run WQNet= 0
Run RASMapper=-1
UNET Theta= 0
UNET Theta Warmup= 0
UNET ZTol= 0
UNET ZSATol= 0
UNET MxIter= 0
UNET Max Iter WO Improvement= 0
UNET MaxInSteps= 0
UNET DtIC= 0
UNET DtMin= 0
UNET MaxCRTS= 0
UNET WFStab= 0
UNET SFStab= 0
UNET WFX= 1
UNET SFX= 1
UNET Gravity=32.17405
UNET 1D Methodology=Finite Difference
UNET DSS MLevel= 1
UNET Pardiso=0
UNET DZMax Abort= 0
UNET Use Existing IB Tables= 0
UNET Froude Reduction=False
UNET Froude Limit= 0
UNET Froude Power= 0
UNET D1 Cores= 0
UNET WindReference=Eulerian
UNET WindDragFormulation=Hsu (1988)
UNET D2 Coriolis=0
UNET D2 Cores= 0
UNET D2 Theta= 1
UNET D2 Theta Warmup= 1
UNET D2 Z Tol= 0.01
UNET D2 Volume Tol= 0.01
UNET D2 Max Iterations= 20
UNET D2 Equation= 0
UNET D2 RampUpFraction=0.1
UNET D2 TimeSlices= 1
UNET D2 Turbulence Formulation=Non-Conservative (original)
UNET D2 Eddy Viscosity=0.3
UNET D2 Transverse Eddy Viscosity=0.1
UNET D2 Smagorinsky Mixing=0
UNET D2 BCVolumeCheck=0
UNET D2 Cores=0
UNET D2 SolverType=PARDISO (Direct)
UNET D2 Minimum Iterations= 3
UNET D2 Maximum Iterations= 30
UNET D2 Restart Number= 10
UNET D2 Relaxation Coeff=1.3
UNET D2 SOR Precondition Iterations= 10
UNET D2 ILUT Maximum Fill= 8
UNET D2 ILUT Tolerance=1E-08
UNET D2 Convergence Tolerance=0.00001
UNET D1D2 MaxIter= 0
UNET D1D2 ZTol=0.01
UNET D1D2 QTol=0.1
UNET D1D2 MinQTol=1
Write IC File= 0
Write IC File at Fixed DateTime=0
Write IC File at Sim End=0
Echo Input=False
Echo Parameters=False
Echo Output=False
Write Detailed= 0
HDF Write Warmup=0
HDF Write Time Slices=0
HDF Flush=0
HDF Compression= 1
HDF Chunk Size= 1
HDF Spatial Parts= 1
HDF Use Max Rows=0
HDF Fixed Rows= 1
Calibration Method= 0
Calibration Iterations= 20
Calibration Max Change=0.05
Calibration Tolerance=0.2
Calibration Maximum=1.5
Calibration Minimum=0.5
Calibration Optimization Method= 1
WQ AD Non Conservative
WQ ULTIMATE=-1
WQ Max Comp Step=1HOUR
WQ Output Interval=15MIN
WQ Output Selected Increments= 0
WQ Create Restart=0
WQ Fixed Restart=0
WQ System Summary=0
WQ Write To DSS=0
Sorting and Armoring Iterations= 10
XS Update Threshold= 0.02
Bed Roughness Predictor= 0
Hydraulics Update Threshold= 0.02
Energy Slope Method= 1
Volume Change Method= 1
Sediment Retention Method= 0
Sediment TS Multiplier= 1
Warm Up Method= 0
XS Weighting Method= 0
Number of US Weighted Cross Sections= 1
Number of DS Weighted Cross Sections= 1
Upstream XS Weight=0
Main XS Weight=1
Downstream XS Weight=0
Number of DS XS's Weighted with US Boundary= 1
Upstream Boundary Weight= 1
Weight of XSs Associated with US Boundary= 0
Number of US XS's Weighted with DS Boundary= 1
Downstream Boundary Weight= 0.5
Weight of XSs Associated with DS Boundary= 0.5
Percentile Method= 0
Sediment Output Level= 3
Mass or Volume Output= 0
Output Increment Type= 1
Profile and TS Output Increment= 1
Transport Output Increment 1
XS Output Flag= 0
XS Output Increment= 10
Read HDF5 Sediment Hotstart= 0
Sediment Hotstart Type= 0
Write Gradation File= 0
Read Gradation Hotstart= 0
Write HDF5 File= 1
Write Binary Output= 1
Write DSS Sediment File= 0
DSS Sediment Output Type= 1
SV Curve= 0
Specific Gage Flag= 0
Subcell Erosion Methods= 0
Subcell Deposition Methods= 0
Advection Scheme= 1
Matrix Solver= 0
Implicit Weighting Factor= 1
Maximum Outer Loop Convergence Iterations= 5
Convergence Maximum Absolute= 0.001
Convergence RMSE= 0.0001
Grain Fractions Max Abs Error= 0.001
Max Subgrid Regions= 1
Max Subgrid Length Scale= 3.402823E+38
Initial Layer Thickness= 3.402823E+38
Min Layer Thickness= 3.402823E+38
Max Layer Thickness= 3.402823E+38
Number of Layers= 5

--- TENMILECK.f01 (steady flow) ---

Flow Title=Flows
Program Version=6.31
Number of Profiles= 1
Profile Names=01pct
River Rch & RM=TENMILECK,Main,20290
     415
River Rch & RM=TENMILECK,Main,15932
     463
River Rch & RM=TENMILECK,Main,12830
     546
River Rch & RM=TENMILECK,Main,12214
     627
River Rch & RM=TENMILECK,Main,10270
     698
River Rch & RM=TENMILECK,Main,4987
     790
River Rch & RM=TENMILECK,Main,3490
    1590
Boundary for River Rch & Prof#=TENMILECK,Main            , 1
Up Type= 0
Dn Type= 3
Dn Slope=0.00709
DSS Import GetInterval= 0
DSS Import GetPeak= 0
DSS Import FillOption= 0

--- TENMILECK.g01 (geometry) ---

Geom Title=Geometry
Program Version=6.31

River Reach=TENMILECK       ,Main
Reach XY= 30
2207194.65525668 679268.63977349     2207669.472      679939.564
     2207800.106      680690.486      2208722.24      681351.811
      2208811.58      681726.686     2208807.917      682385.807
     2208410.522      682598.141     2208584.223      683631.621
     2208477.255      684106.739     2207889.932      685338.475
     2207564.535      685283.703     2207143.302      685532.351
     2206717.633      685377.593      2206620.71      685513.235
     2205313.828      685233.481     2204795.843      684947.403
     2204448.497      684631.249     2204482.293      684458.006
     2203137.523      683589.527     2203372.149      683359.737
     2203097.059      683074.947     2203396.759      682937.474
      2203232.73      682517.213     2202929.596      682334.898
     2202770.747      682442.525     2202283.181      682026.414
     2201630.985      682148.606     2200619.796        683390.9
     2200136.637      683498.441     2199759.816      683069.939

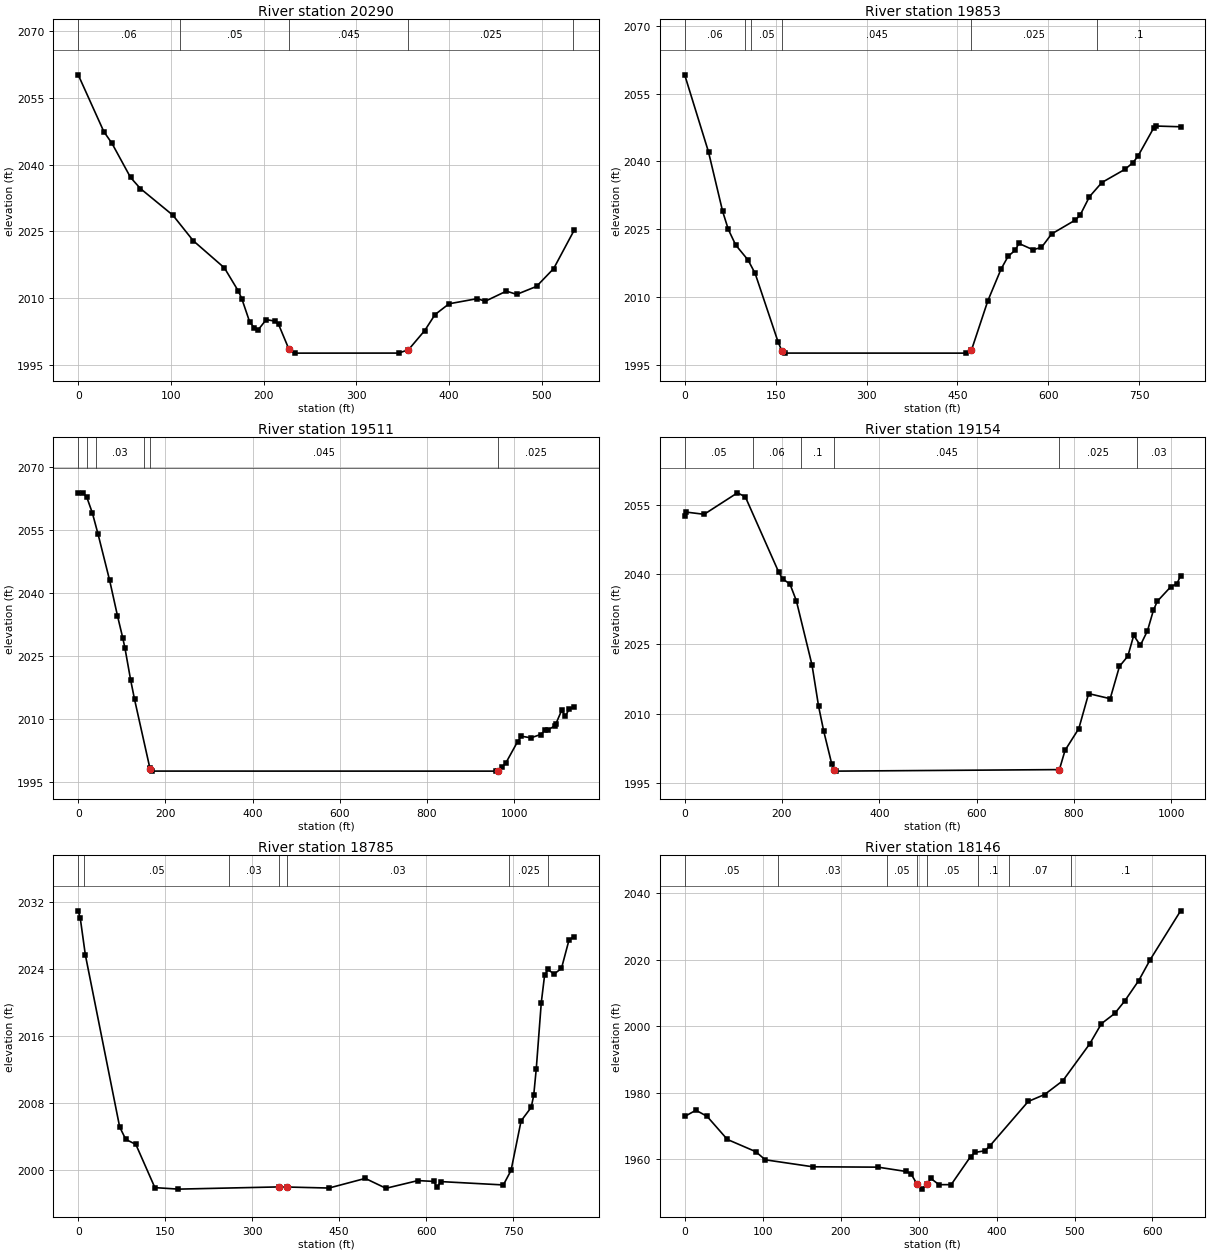
Type RM Length L Ch R = 1 ,20290   ,458.7,436.9,439.5
XS GIS Cut Line= 3
 2206930.9643152679408.186896529 2207317.3241762 679235.69579858
2207422.34117572679197.646161074
#Sta/Elev= 30
       0 2060.24    27.6 2047.47    36.4 2044.82    56.4 2037.16      67 2034.66
   102.1 2028.65     124 2022.92   157.6 2016.81   172.8 2011.54   176.5 2009.81
   184.9 2004.63   189.7 2003.37   194.1 2002.88   202.8 2005.16   212.2 2004.82
     216 2004.12   227.3 1998.46   233.5 1997.62   345.4 1997.63   356.1 1998.37
   373.7 2002.71   384.8  2006.3   399.9 2008.72   430.3 2009.88   438.9 2009.29
   461.7 2011.57   472.9 2010.84   494.2 2012.63   512.7 2016.64   534.8 2025.27
#Mann= 5 ,-1,0
       0     .06       0     110     .05       0   227.3    .045       0
   356.1    .025       0  533.12      .1       0
Bank Sta=227.3,356.1
XS Rating Curve= 0 ,0
Exp/Cntr(USF)=0,0
Exp/Cntr=0.3,0.1

Type RM Length L Ch R = 1 ,19853   ,312.3,341.6,637.1
XS GIS Cut Line= 3
2207134.37812662679834.6530188912207722.65499709679484.692114924
2207768.95106991679359.360131863
#Sta/Elev= 30
       0 2059.13    39.3 2042.09    62.6 2028.96    71.9 2024.99    84.1 2021.53
   104.5  2018.2   116.2 2015.25   154.1 2000.09   160.3 1998.11     165 1997.63
   463.5 1997.62   472.91998.208   500.1 2009.19   521.8 2016.17   533.5 2019.01
   545.2 2020.36   551.3 2021.87   574.4 2020.48   588.5 2020.97   605.3 2023.96
   644.4 2027.03   652.3 2028.11   667.7 2032.19   688.2 2035.33   726.6 2038.27
   739.4 2039.72   747.6 2041.12   773.5 2047.35   777.8 2047.81   818.1 2047.65
#Mann= 6 ,-1,0
       0     .06       0     100     .07       0     110     .05       0
   160.3    .045       0   472.9    .025       0     680      .1       0
Bank Sta=160.3,472.9
XS Rating Curve= 0 ,0
Exp/Cntr(USF)=0,0
Exp/Cntr=0.3,0.1

Type RM Length L Ch R = 1 ,19511   ,303.5,356.8,557.4
XS GIS Cut Line= 3
     2207286.568      680086.797     2207659.305      679917.216
2208322.38651954679615.801276243
#Sta/Elev= 30
       0 2063.76    10.6 2063.71    19.3 2062.83    32.5 2058.96    45.7 2053.87
    72.1 2042.96      90 2034.57   102.1 2029.32   107.2 2026.88   120.2 2019.33
   129.2 2014.69   164.4 1998.34   165.5 1998.03   168.6 1997.63   959.7 1997.62
   962.4 1997.76   972.9 1998.59   981.7 1999.66    1008  2004.6  1016.8 2005.92
  1038.8 2005.53  1060.7 2006.32  1071.7  2007.3  1078.3 2007.43  1092.9 2008.36
  1095.9 2008.84  1109.1 2012.03  1117.9 2010.72  1126.7 2012.42  1137.9 2012.85
#Mann= 6 ,-1,0
       0     .05       0      20     .06       0      40     .03       0
     150     .05       0   165.5    .045       0   962.4    .025       0
Bank Sta=165.5,962.4
XS Rating Curve= 0 ,0
Exp/Cntr=0.3,0.1

Type RM Length L Ch R = 1 ,19154   ,405.5,369.7,480.8
XS GIS Cut Line= 2
2207284.52085596680321.6027773932208295.75013328680192.163055903
#Sta/Elev= 30
       0 2052.55     3.7 2053.44      40 2052.97   108.5  2057.6   124.7 2056.73
   193.1 2040.55   201.3 2039.07   216.5 2037.92   229.5 2034.36   261.8 2020.47
   275.3 2011.58   285.8 2006.25   302.1 1999.26   307.81997.956   310.2 1997.62
   770.31997.949     782 2002.12   810.2 2006.79   830.4 2014.33   874.7 2013.23
   893.8  2020.2     911  2022.4   923.1 2026.88   936.7 2024.72   951.4 2027.88
   963.5 2032.26   971.5 2034.22   999.7  2037.4  1011.9 2037.97  1019.5 2039.77
#Mann= 6 ,-1,0
       0     .05       0     140     .06       0     240      .1       0
   307.8    .045       0   770.3    .025       0     930     .03       0
Bank Sta=307.8,770.3
XS Rating Curve= 0 ,0
Exp/Cntr=0.3,0.1

Type RM Length L Ch R = 1 ,18785   ,641.3,639,637.4
XS GIS Cut Line= 4
2207464.86448645680769.4598030982207760.83987898680642.078383982
2208170.53128903680459.4257197172208248.29240342680426.422970929
#Sta/Elev= 30
       0 2030.93     3.6 2030.02    12.3 2025.67    71.5 2005.12      82 2003.64
    99.4 2003.04   132.2 1997.88   172.7  1997.7   345.71997.964   360.9 1997.95
   432.5 1997.83   495.1 1998.98   530.7  1997.8   585.9 1998.72   613.2 1998.62
   619.1  1997.9   625.3  1998.6   733.2  1998.2   746.5 1999.94   763.8 2005.85
   781.3 2007.47   785.6 2008.93     790  2012.1   798.6 2019.96   804.3 2023.23
   810.4 2023.93   820.4 2023.37   833.4 2024.05   846.4 2027.44   855.3 2027.86
#Mann= 7 ,-1,0
       0     .06       0      10     .05       0     260     .03       0
   345.7    .045       0   360.9     .03       0  742.22    .025       0
  810.79     .03       0
Bank Sta=345.7,360.9
XS Rating Curve= 0 ,0
Exp/Cntr(USF)=0,0
Exp/Cntr=0.3,0.1

Type RM Length L Ch R = 1 ,18146   ,116.3,131.3,104.4
XS GIS Cut Line= 3
2208022.28960122681227.6325401272208279.63647056681011.671851043
2208514.11142341 680824.30079321
#Sta/Elev= 30
       0 1972.84    14.4 1974.72    28.7 1972.89    54.7 1965.93    91.1 1962.25
   103.4 1959.79   164.3 1957.69   247.9 1957.58   284.2 1956.27   290.1 1955.66
   297.91952.496     304 1950.96   310.5  1952.4   315.8 1954.17   326.2  1952.3
   341.8 1952.31   366.6 1960.73   372.3 1962.01   384.8  1962.5   391.2 1963.92
   440.6 1977.36   461.7 1979.46   485.1 1983.63   519.4 1994.67   534.5 2000.79
   551.6 2003.87   564.2 2007.56   582.4 2013.78   597.1 2020.08   636.1 2034.78
#Mann= 8 ,-1,0
       0     .05       0     120     .03       0     260     .05       0
   297.9    .045       0   310.5     .05       0  375.96      .1       0
  415.96     .07       0  495.96      .1       0
Bank Sta=297.9,310.5
XS Rating Curve= 0 ,0
Exp/Cntr(USF)=0,0
Exp/Cntr=0.3,0.1

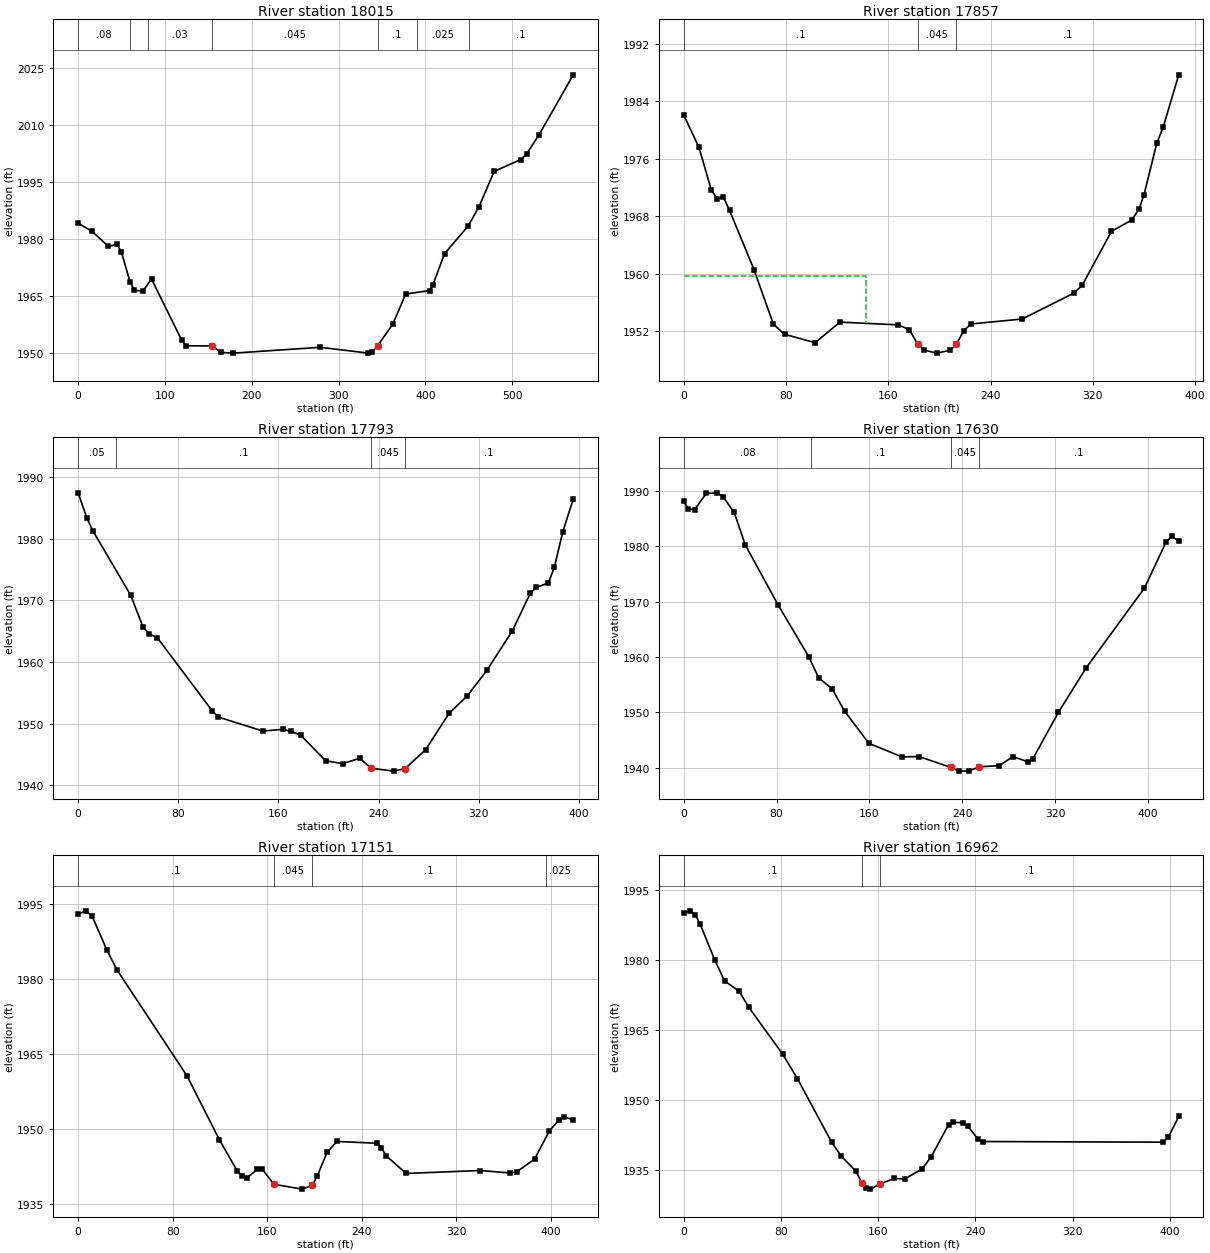
Type RM Length L Ch R = 1 ,18015   ,153.3,157.7,188.6
XS GIS Cut Line= 2
2208174.20711394681321.3034053082208511.95215026680861.594883652
#Sta/Elev= 30
       0 1984.19    15.8 1982.08    34.9  1978.1    44.8 1978.66    49.8 1976.64
    59.7 1968.82    64.7 1966.55    74.6 1966.36    84.5 1969.53   119.3 1953.42
   124.2 1951.95     154 1951.93   164.6 1950.23   178.8 1950.03     279 1951.56
   333.4 1950.06   339.1 1950.36   344.9 1951.93   362.5 1957.66   377.4 1965.57
   404.9 1966.49   408.7 1967.99   422.1 1976.19   449.2 1983.42   461.8  1988.5
   479.3 1997.82     510 2000.95   516.8 2002.47   531.2 2007.51   570.4 2023.22
#Mann= 7 ,-1,0
       0     .08       0      60      .1       0      80     .03       0
     154    .045       0   344.9      .1       0     390    .025       0
     450      .1       0
Bank Sta=154,344.9
XS Rating Curve= 0 ,0
Exp/Cntr(USF)=0,0
Exp/Cntr=0.3,0.1

Type RM Length L Ch R = 1 ,17857   ,103,63.8,72.3
XS GIS Cut Line= 3
2208301.02905881681347.2340450382208364.84828009681249.510862455
2208530.37938528681035.616753639
#Sta/Elev= 30
       0 1982.11      12 1977.57    21.6 1971.67    26.3  1970.4    31.1 1970.65
    35.9 1968.82      55 1960.59    70.2 1952.98    78.9 1951.59   102.8 1950.42
   122.2 1953.28   167.7  1952.9   176.4 1952.25   182.9 1950.28   187.9 1949.39
   198.1 1948.97   208.2 1949.36   213.2 1950.17   219.1 1952.09   224.8 1953.03
   264.7 1953.71   305.2 1957.32   311.7  1958.4   334.6 1965.91   350.3 1967.46
     356 1968.95   359.9  1970.9     370 1978.13   375.1 1980.42   387.2 1987.67
#Mann= 3 ,-1,0
       0      .1       0   182.9    .045       0   213.2      .1       0
#XS Ineff= 2 , 0
          142.65 1959.65
Permanent Ineff=
       F       F
Bank Sta=182.9,213.2
XS Rating Curve= 0 ,0
Exp/Cntr(USF)=0,0
Exp/Cntr=0.3,0.1

Type RM Length L Ch R = 1 ,17793   ,163.9,163.3,167.6
XS GIS Cut Line= 5
2208325.10946037681378.6990042592208392.95842632681288.444164082
2208450.48125832681243.471768158 2208494.3221328681162.004040148
2208559.28240838681064.730454314
#Sta/Elev= 30
       0 1987.46     6.9 1983.39    11.8 1981.28    41.9 1970.87    51.9 1965.65
    56.9 1964.58    63.3 1963.94     107 1952.12     112 1951.09   147.5 1948.83
   163.7 1949.11   170.2 1948.77   177.9 1948.12   197.6 1944.02   211.2 1943.54
   224.9 1944.41     234  1942.8   252.1 1942.33   261.2 1942.75   277.5  1945.8
   296.2 1951.69   310.6  1954.5   326.5 1958.69   346.8 1965.09   361.2 1971.22
     366 1972.14   375.6 1972.84   380.4 1975.45   387.1 1981.17   395.4 1986.43
#Mann= 4 ,-1,0
       0     .05       0      30      .1       0     234    .045       0
   261.2      .1       0
Bank Sta=234,261.2
XS Rating Curve= 0 ,0
Exp/Cntr=0.3,0.1

Type RM Length L Ch R = 1 ,17630   ,455.6,478.9,477.5
XS GIS Cut Line= 3
2208442.91730962681513.296331092 2208637.5182432681223.328052583
2208683.91316776681161.468153168
#Sta/Elev= 30
       0 1988.08     3.9 1986.73     9.4 1986.56    19.4 1989.49      29 1989.61
    33.9 1988.92    43.5 1986.08    53.1 1980.21    81.2 1969.44   107.7 1960.08
   116.3 1956.23   127.8 1954.27   138.6 1950.24   159.5 1944.42     188 1941.97
   202.8 1942.03   230.2 1940.07   237.4  1939.4   245.8 1939.43   254.7 1940.19
     272 1940.38   283.5 1942.01   296.6 1941.09   300.8 1941.61   322.9 1950.02
   346.9 1958.08   396.9 1972.41   415.5 1980.67   420.3 1981.74   426.5 1980.93
#Mann= 4 ,-1,0
       0     .08       0     110      .1       0   230.2    .045       0
   254.7      .1       0
Bank Sta=230.2,254.7
XS Rating Curve= 0 ,0
Exp/Cntr(USF)=0,0
Exp/Cntr=0.3,0.1

Type RM Length L Ch R = 1 ,17151   ,184.2,188.3,195.2
XS GIS Cut Line= 3
2208617.13712467681670.448684867 2208811.6130497681602.804884856
2209015.48394696 681540.79806818
#Sta/Elev= 30
       0 1992.91     6.5 1993.59    11.7  1992.6    24.4 1985.71    32.9 1981.79
    92.2 1960.59   119.6 1947.84   134.5 1941.71   138.5 1940.68     143 1940.28
   151.4 1941.93   155.7 1942.05   165.71938.971   189.6 1938.01     198 1938.74
   202.3 1940.59   210.7 1945.38     219 1947.53   252.5 1947.18   256.7 1946.24
   260.8 1944.64   277.6 1941.14   340.3 1941.73   365.4 1941.24   371.2 1941.49
   386.3 1943.99   398.8 1949.64   407.2 1951.88   411.4 1952.48     419 1951.79
#Mann= 4 ,-1,0
       0      .1       0   165.7    .045       0     198      .1       0
   395.9    .025       0
Bank Sta=165.7,198
XS Rating Curve= 0 ,0
Exp/Cntr(USF)=0,0
Exp/Cntr=0.3,0.1

Type RM Length L Ch R = 1 ,16962   ,145.9,149.7,150.6
XS GIS Cut Line= 3
2208642.66149289681802.1174807722208837.86813798681791.678622746
2209048.73307011681771.844792496
#Sta/Elev= 30
       0 1990.09     5.5 1990.45     9.5 1989.65    13.5 1987.64    25.5 1980.01
    33.6 1975.48    45.6 1973.27    53.6 1969.84    81.6 1959.77    93.6 1954.59
   121.7 1941.03   129.7 1938.02   141.7 1934.81   146.8 1932.22   149.7  1931.2
   153.7 1930.98   161.51932.095   173.4 1933.27   181.8 1933.13   196.2 1935.29
   203.6 1937.87   217.9 1944.75   221.9 1945.22   229.9 1945.19     234 1944.39
     242 1941.69     246 1941.15   394.7 1941.01   398.7 1942.06   407.3  1946.5
#Mann= 3 ,-1,0
       0      .1       0   146.8    .045       0   161.5      .1       0
Bank Sta=146.8,161.5
XS Rating Curve= 0 ,0
Exp/Cntr(USF)=0,0
Exp/Cntr=0.3,0.1

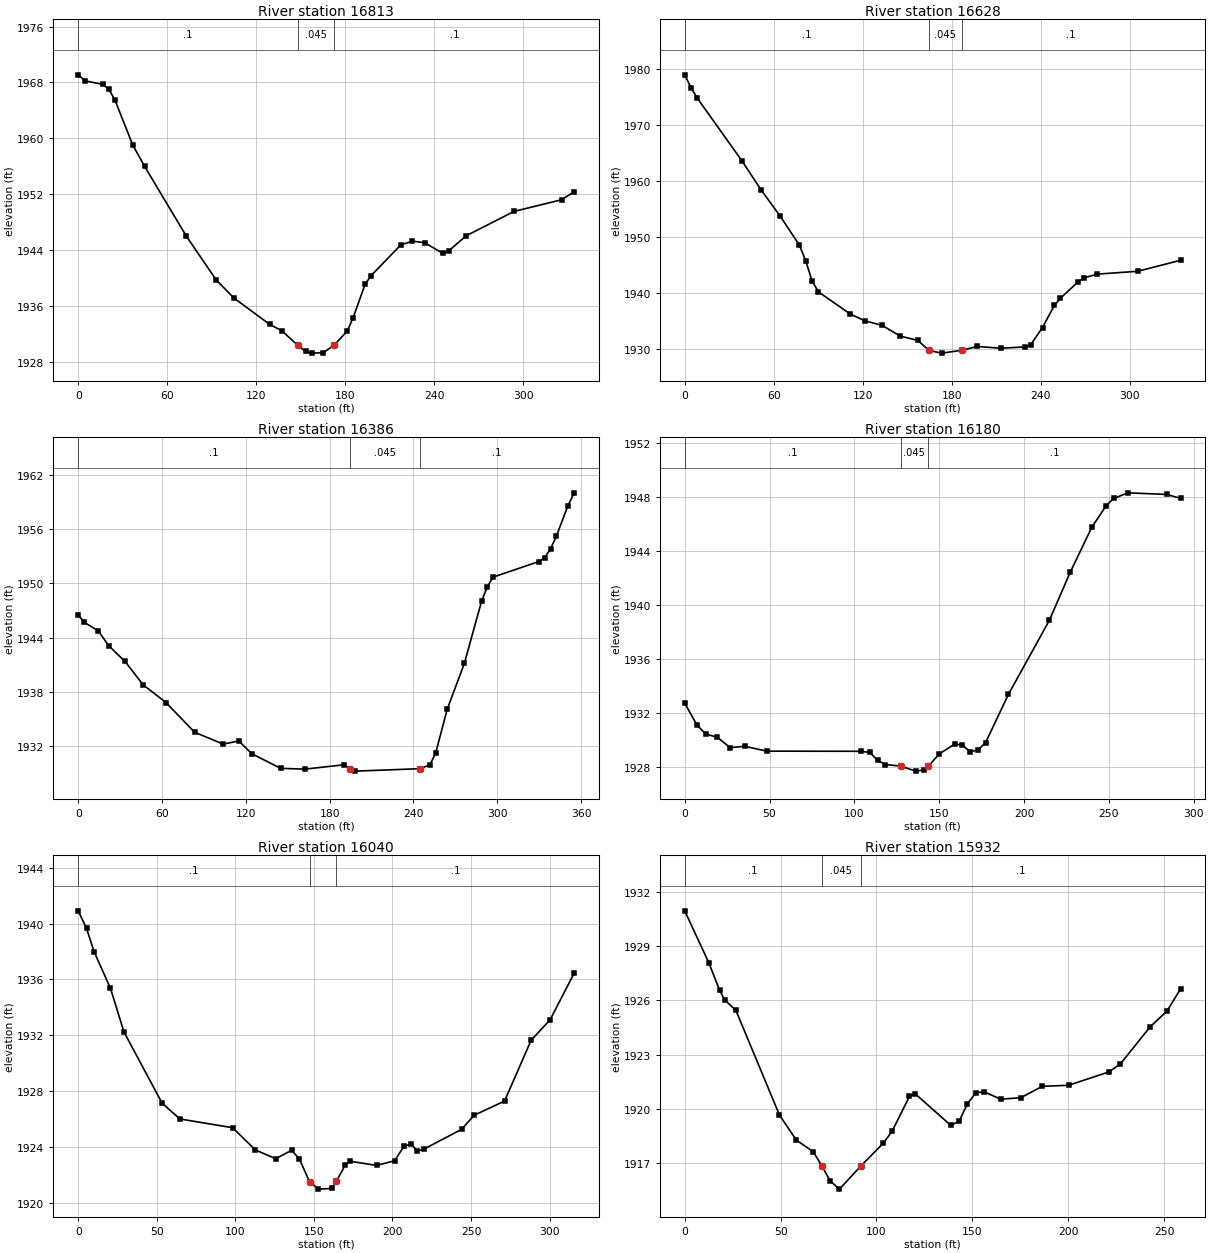
Type RM Length L Ch R = 1 ,16813   ,183.3,184.3,174.4
XS GIS Cut Line= 2
2208639.52983548681916.9449190622208972.52940652681947.217607338
#Sta/Elev= 30
       0 1969.09     4.7 1968.22    16.7 1967.72    20.7 1966.99    24.7 1965.52
    36.8 1959.03    44.8 1955.97    72.9    1946      93 1939.74   105.1 1937.12
   129.2 1933.35   137.2 1932.47   148.1 1930.35   153.3 1929.49   157.3 1929.25
   165.3 1929.31   172.8 1930.44   181.4 1932.42   185.4 1934.33   193.4 1939.09
   197.5 1940.35   217.5 1944.74   225.4 1945.28   233.6 1945.06   245.7 1943.55
   249.7 1943.87   261.7 1946.06   293.9 1949.54     326 1951.21   334.4 1952.35
#Mann= 3 ,0,0
       0      .1       0   148.1    .045       0   172.8      .1       0
Bank Sta=148.1,172.8
XS Rating Curve= 0 ,0
Exp/Cntr(USF)=0,0
Exp/Cntr=0.3,0.1

Type RM Length L Ch R = 1 ,16628   ,226.1,242.8,255.7
XS GIS Cut Line= 3
2208576.11672352682045.176266065 2208700.7102052682093.683618464
2208901.18699549682086.166731082
#Sta/Elev= 30
       0 1978.96     4.4  1976.6     8.6 1974.76    38.7 1963.56    51.6 1958.38
    64.4 1953.72    77.3 1948.56    81.6 1945.74    85.9 1942.15    90.2 1940.19
   111.7 1936.25   121.3 1935.05   133.1 1934.23   145.2 1932.32   157.2 1931.54
   164.61929.751   173.2 1929.27   186.7 1929.77   197.2 1930.46   213.2 1930.14
   229.2 1930.38   233.2 1930.75   241.2 1933.84   249.2  1937.8   253.2 1939.05
   265.3 1942.02   269.3 1942.71   278.2 1943.38   305.3 1943.88   334.3 1945.85
#Mann= 3 ,-1,0
       0      .1       0   164.6    .045       0   186.7      .1       0
Bank Sta=164.6,186.7
XS Rating Curve= 0 ,0
Exp/Cntr(USF)=0,0
Exp/Cntr=0.3,0.1

Type RM Length L Ch R = 1 ,16386   ,190.7,205.4,223.9
XS GIS Cut Line= 3
2208594.87958442682241.2243683322208693.80864194682263.208603335
2208940.70851197682321.551380844
#Sta/Elev= 30
       0  1946.5     4.4 1945.69    14.5 1944.71    21.8 1943.09    33.4 1941.36
    46.4 1938.76    62.8 1936.78    83.3 1933.48   103.8 1932.16   114.9 1932.51
   124.3 1931.09   144.9 1929.47   162.1 1929.38   190.1 1929.86   194.7 1929.44
   198.3 1929.16   244.6 1929.43   251.7 1929.86   255.8 1931.12   264.1 1936.02
   276.4 1941.12   288.7 1948.01   292.8 1949.62     297 1950.71   329.8 1952.44
   333.9 1952.88   338.1 1953.84   342.2 1955.22   350.4 1958.58     355 1960.07
#Mann= 3 ,0,0
       0      .1       0   194.7    .045       0   244.6      .1       0
Bank Sta=194.7,244.6
XS Rating Curve= 0 ,0
Exp/Cntr(USF)=0,0
Exp/Cntr=0.3,0.1

Type RM Length L Ch R = 1 ,16180   ,145.3,140.7,134.2
XS GIS Cut Line= 4
2208640.05745949 682335.549977062208705.22481826682416.598748794
2208742.92294883682486.9030884912208845.52911974682522.166364295
#Sta/Elev= 30
       0 1932.73     7.2 1931.11    12.4 1930.44    19.3 1930.19    26.8 1929.43
    35.4 1929.53    48.3 1929.17     104 1929.16   109.2 1929.07   113.7 1928.48
   118.3 1928.18   127.3 1928.06   136.2 1927.69     141 1927.78   143.51928.035
     150 1928.96   159.1 1929.69   163.7 1929.62   168.2 1929.13   172.7 1929.25
   177.3 1929.79   190.8 1933.37   214.9 1938.85   227.2 1942.41     240 1945.76
   248.5 1947.36   252.8 1947.88   261.2  1948.3   284.1 1948.18   292.3 1947.89
#Mann= 3 ,-1,0
       0      .1       0   127.3    .045       0   143.5      .1       0
Bank Sta=127.3,143.5
XS Rating Curve= 0 ,0
Exp/Cntr=0.3,0.1

Type RM Length L Ch R = 1 ,16040   ,109.9,107.9,105.4
XS GIS Cut Line= 4
2208508.12921426 682384.796339122208582.73066891682495.975498716
2208644.00759563 682543.856978042208747.43037451682554.635427117
#Sta/Elev= 30
       0 1940.91     5.3 1939.65    10.1 1937.98    20.5 1935.36    29.1 1932.23
    53.4 1927.12    64.7 1925.99    98.3 1925.36   112.7 1923.77   125.7 1923.14
   135.8 1923.75   140.8 1923.11   147.2 1921.49   152.9 1920.96   161.4 1921.01
   164.3 1921.53     170  1922.7   172.8 1922.96   189.9 1922.66   201.3 1922.99
   207.3 1924.03   211.8  1924.2   215.8 1923.69   219.9 1923.82     244 1925.25
     252 1926.26   271.3 1927.27   288.2 1931.63   300.3  1933.1   315.6 1936.44
#Mann= 3 ,-1,0
       0      .1       0   147.2    .045       0   164.3      .1       0
Bank Sta=147.2,164.3
XS Rating Curve= 0 ,0
Exp/Cntr(USF)=0,0
Exp/Cntr=0.3,0.1

Type RM Length L Ch R = 1 ,15932   ,141.4,139.7,136.9
XS GIS Cut Line= 4
2208456.87585733682486.7293517672208491.14474881682519.338651444
2208546.58729839682550.6830972752208682.72044592682607.757553536
#Sta/Elev= 30
       0 1930.94    12.6 1928.07    18.2 1926.55      21    1926    26.7 1925.44
    49.4 1919.66    58.2 1918.27      67 1917.63    71.5 1916.85    75.8 1916.02
    80.7 1915.56    91.7 1916.82   103.6  1918.1   108.2 1918.77   117.2 1920.68
   120.2 1920.83   138.7 1919.09   143.1 1919.31   147.4 1920.27   151.8 1920.88
   156.1 1920.94   164.8 1920.53   175.2 1920.61   186.5 1921.24   200.2  1921.3
   221.3 1922.04   227.2 1922.48   242.8 1924.54   251.5  1925.4   258.6 1926.63
#Mann= 3 ,-1,0
       0      .1       0    71.5    .045       0    91.7      .1       0
Bank Sta=71.5,91.7
XS Rating Curve= 0 ,0
Exp/Cntr=0.3,0.1

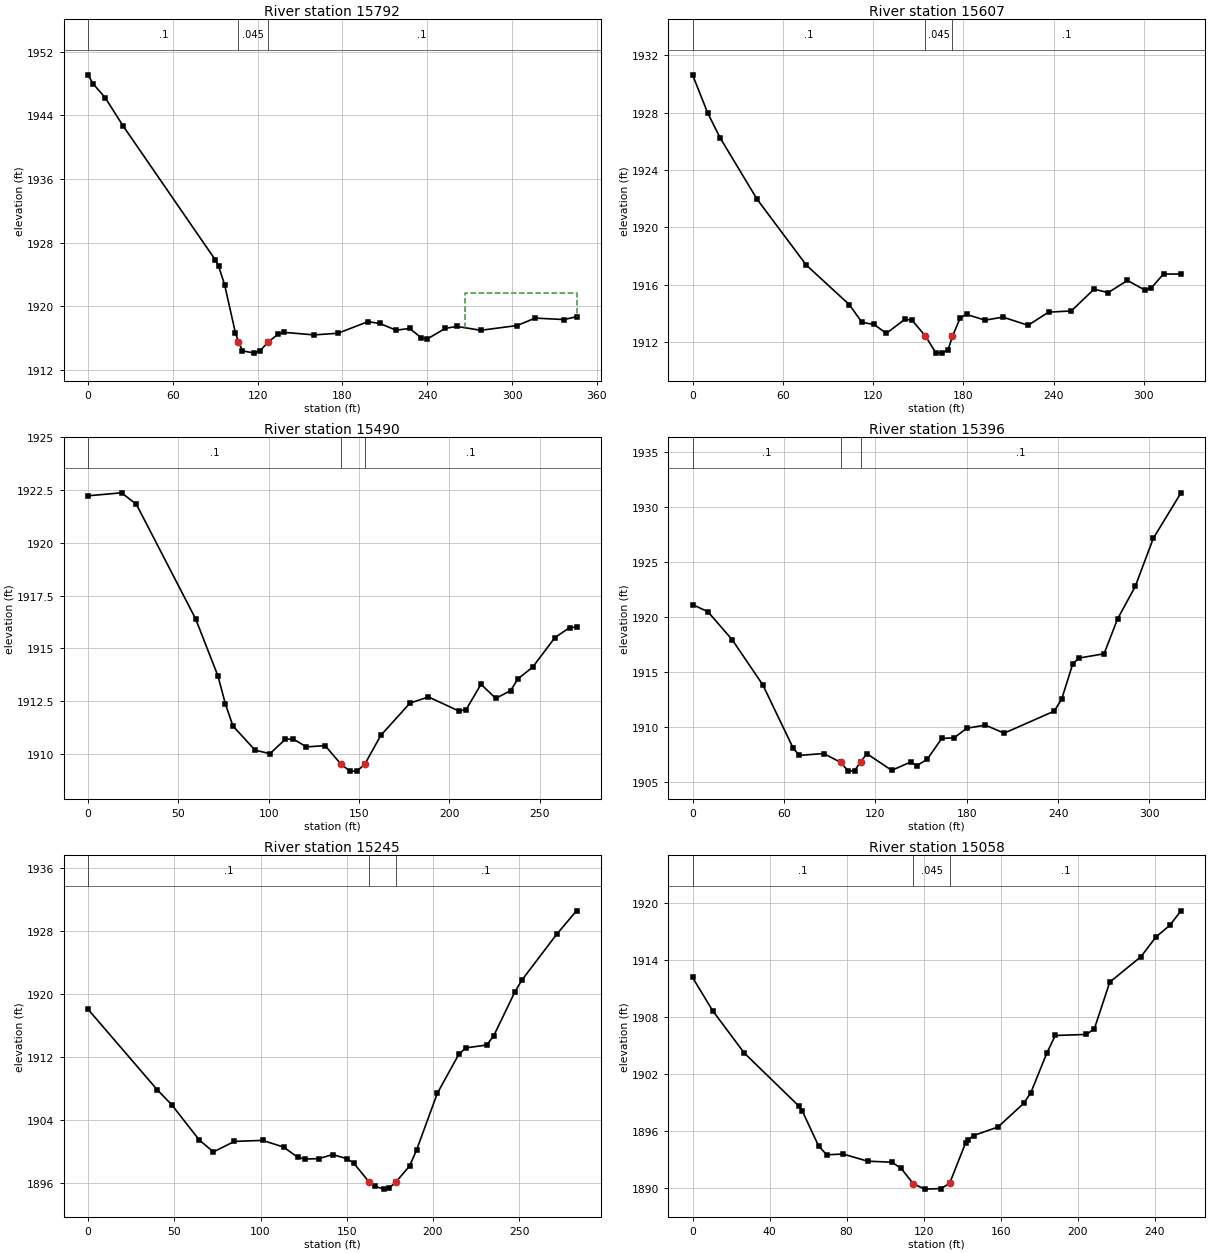
Type RM Length L Ch R = 1 ,15792   ,184.8,184.9,181.6
XS GIS Cut Line= 3
2208300.77011045682552.1785037992208491.55635023682617.144285664
2208628.55025248682661.786513075
#Sta/Elev= 30
       0 1949.09     3.5 1947.97      12 1946.24    24.7 1942.69      90 1925.84
    92.3 1925.08    96.6 1922.71   104.3 1916.62   106.4 1915.57   109.2 1914.41
   117.7 1914.12   121.9 1914.45   127.2 1915.48   134.6 1916.53   138.8 1916.73
   159.9 1916.41   176.8 1916.62     198 1918.07   206.4 1917.85   217.9    1917
   227.5 1917.22   235.9 1916.03   240.1 1915.91   252.8 1917.24   261.1 1917.47
   277.9 1916.99   303.6 1917.59   316.3 1918.52   336.8 1918.34   345.6  1918.7
#Mann= 3 ,-1,0
       0      .1       0   106.4    .045       0   127.2      .1       0
#XS Ineff= 2 , 0
                          266.99         1921.62
Permanent Ineff=
       F       F
Bank Sta=106.4,127.2
XS Rating Curve= 0 ,0
Exp/Cntr(USF)=0,0
Exp/Cntr=0.3,0.1

Type RM Length L Ch R = 1 ,15607   ,125.8,117.2,108.1
XS GIS Cut Line= 3
2208302.30566646  682705.45956342208584.63397676 682767.09997616
2208619.63964326682773.948910911
#Sta/Elev= 30
       0 1930.63    10.1 1927.96    18.3 1926.24    42.9 1921.95    75.6 1917.36
   104.3 1914.59   112.5 1913.37   120.6 1913.22   128.8  1912.6   141.1 1913.58
   145.8 1913.52   154.7 1912.42   161.6 1911.26   165.7 1911.22   169.8 1911.45
   172.7 1912.39     178  1913.7   182.1 1913.92   194.3 1913.52   206.3 1913.73
     223 1913.16   236.6 1914.08   251.7 1914.16   266.8 1915.68   276.2 1915.44
     289 1916.29   300.7 1915.61   304.8 1915.76     313 1916.74   324.6 1916.73
#Mann= 3 ,-1,0
       0      .1       0   154.7    .045       0   172.7      .1       0
Bank Sta=154.7,172.7
XS Rating Curve= 0 ,0
Exp/Cntr=0.3,0.1

Type RM Length L Ch R = 1 ,15490   ,89.5,93.6,97.6
XS GIS Cut Line= 4
2208354.18332457682886.5189951472208457.28315693682862.032784961
2208538.47427491682824.6590957312208611.93290547682809.194120877
#Sta/Elev= 30
       0 1922.23    18.5 1922.37    26.7 1921.83    59.6 1916.38    71.9 1913.68
      76 1912.36    80.2 1911.31    92.5 1910.16   100.7    1910   109.2 1910.68
   113.6 1910.69   120.9 1910.32   131.2 1910.38     140  1909.5     145 1909.17
   148.8 1909.17   153.2  1909.5     162 1910.86   178.1 1912.39   188.4 1912.69
   205.3 1912.02   209.3 1912.09   217.5 1913.29   225.7 1912.62   233.9 1912.99
     238 1913.55   246.1  1914.1   258.4  1915.5   266.6 1915.98   270.4    1916
#Mann= 3 ,0,0
       0      .1       0     140    .045       0   153.2      .1       0
Bank Sta=140,153.2
XS Rating Curve= 0 ,0
Exp/Cntr(USF)=0,0
Exp/Cntr=0.3,0.1

Type RM Length L Ch R = 1 ,15396   ,116.8,151.2,123.4
XS GIS Cut Line= 4
2208386.02595604682938.1818055752208475.37064651682938.181805575
2208504.17975078682933.4410668972208701.46741423682977.566403823
#Sta/Elev= 30
       0 1921.09    10.1 1920.44    26.1 1917.88    46.1  1913.8    66.1 1908.03
    70.1 1907.38    86.1 1907.55    97.2 1906.75   102.3 1905.95   106.4 1905.99
   110.4 1906.81   114.5 1907.53   130.8 1906.02   143.1 1906.77   147.2 1906.45
     154 1907.01   163.6 1908.92   171.8 1908.98     180 1909.85   192.3 1910.13
   204.6  1909.4   237.4  1911.4   242.3 1912.47   249.7 1915.73   253.8 1916.23
   270.2 1916.62   279.1  1919.8   290.7 1922.75   302.5 1927.11   320.7 1931.25
#Mann= 3 ,-1,0
       0      .1       0    97.2    .045       0   110.4      .1       0
Bank Sta=97.2,110.4
XS Rating Curve= 0 ,0
Exp/Cntr(USF)=0,0
Exp/Cntr=0.3,0.1

Type RM Length L Ch R = 1 ,15245   ,187.9,187.1,193.4
XS GIS Cut Line= 2
2208380.56182248683029.3602627912208659.42798711683079.233935955
#Sta/Elev= 30
       0 1918.11    40.2 1907.87    48.4 1906.02    64.6 1901.49    72.7 1900.01
    84.9 1901.34   101.2 1901.47   113.4 1900.62   121.5 1899.34   125.6  1899.1
   133.7 1899.15   141.8 1899.66     150 1899.16     154  1898.6     163 1896.18
   166.2 1895.63   171.9 1895.28   174.3 1895.36   178.4 1896.14   186.5 1898.23
   190.6 1900.29   202.6 1907.47     215 1912.39     219 1913.21   231.2 1913.58
   235.3 1914.76   247.5 1920.31   251.5 1921.79   271.8 1927.65   283.3 1930.62
#Mann= 3 ,-1,0
       0      .1       0     163    .045       0   178.4      .1       0
Bank Sta=163,178.4
XS Rating Curve= 0 ,0
Exp/Cntr(USF)=0,0
Exp/Cntr=0.3,0.1

Type RM Length L Ch R = 1 ,15058   ,240.9,231.4,223.2
XS GIS Cut Line= 3
2208366.40661583683188.775863241 2208545.8505853 683251.72217714
 2208608.7968992683243.266702138
#Sta/Elev= 30
       0 1912.12    10.4 1908.64    26.8 1904.19    55.1 1898.62      57 1898.07
    65.5 1894.39    69.7 1893.47    78.2 1893.55    90.9  1892.8   103.6 1892.69
   108.4 1892.03   114.7 1890.41   120.6 1889.86     129 1889.92   133.5 1890.46
   141.8 1894.71   142.9 1894.99     146  1895.5   158.6 1896.39     172 1898.88
   175.7    1900   184.1 1904.21   188.4 1906.02   204.6 1906.13   208.7 1906.72
   216.7 1911.63   232.9 1914.31   240.7 1916.38   247.9 1917.61   253.7 1919.13
#Mann= 3 ,0,0
       0      .1       0   114.7    .045       0   133.5      .1       0
Bank Sta=114.7,133.5
XS Rating Curve= 0 ,0
Exp/Cntr(USF)=0,0
Exp/Cntr=0.3,0.1

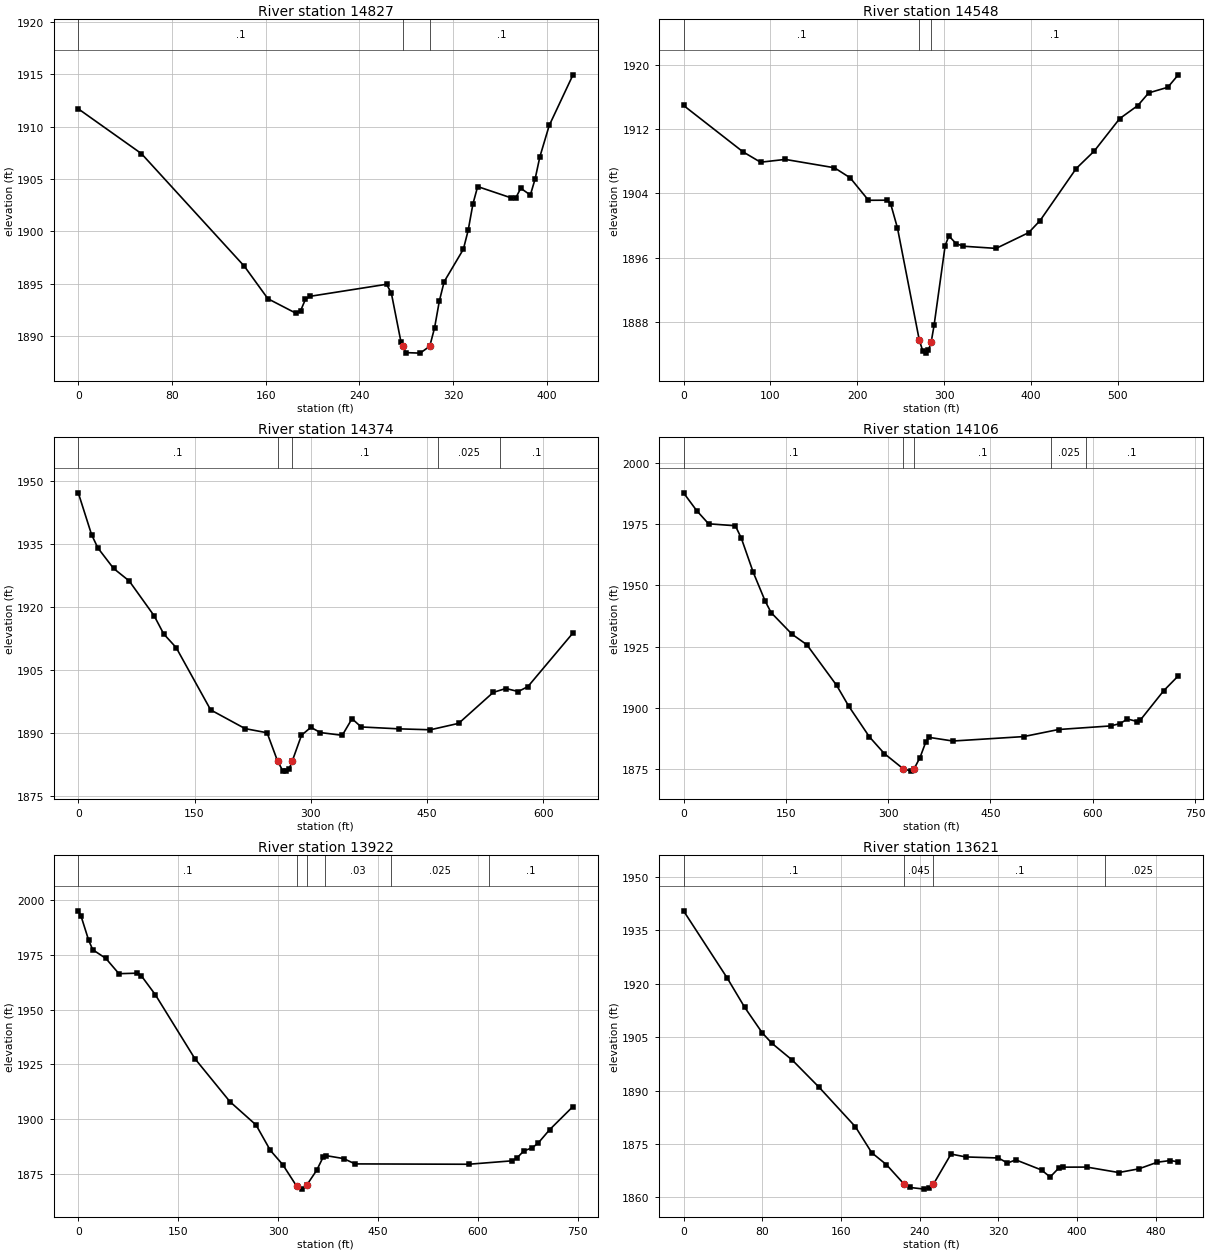
Type RM Length L Ch R = 1 ,14827   ,271.8,278.9,284.1
XS GIS Cut Line= 4
 2208246.3239413683464.183608199 2208456.1476328683462.031414888
2208572.82439782683435.5139682932208663.86763113683416.951755677
#Sta/Elev= 30
       0  1911.7    53.9 1907.42   141.9 1896.64   161.9 1893.55   185.9 1892.16
   189.9 1892.42   193.9 1893.48   197.9 1893.78   263.2 1894.93   267.3 1894.09
   275.5 1889.43   276.91889.076   279.6  1888.4   291.9 1888.35   300.1 1889.01
   304.2 1890.76   308.3 1893.34   312.4 1895.18   328.8 1898.28   332.9 1900.09
     337 1902.63     341 1904.27   369.6 1903.19   373.7 1903.22   377.8 1904.11
     386 1903.46   390.1 1905.02   394.1 1907.11   402.1 1910.11   422.4 1914.95
#Mann= 3 ,-1,0
       0      .1       0   276.9    .045       0   300.1      .1       0
Bank Sta=276.9,300.1
XS Rating Curve= 0 ,0
Exp/Cntr(USF)=0,0
Exp/Cntr=0.3,0.1

Type RM Length L Ch R = 1 ,14548   ,177.2,174.2,172.1
XS GIS Cut Line= 3
 2208292.3990657683663.0341450772208523.38106814683697.457018581
2208844.69443565683795.669783747
#Sta/Elev= 30
       0 1914.94    68.5 1909.16    88.7 1907.87   117.1 1908.22   173.7 1907.18
   191.8 1905.93   212.9 1903.13   234.4 1903.14   238.5 1902.67   246.3 1899.67
   271.41885.721   275.6 1884.31   278.8  1884.1     282 1884.48   285.2 1885.54
   288.4 1887.54   301.2  1897.5   305.5 1898.69   313.8 1897.73   322.2 1897.41
   359.8 1897.14   397.3  1899.1   410.5 1900.61     452 1907.08   472.8 1909.26
   502.1  1913.3     523 1914.93   535.5  1916.5   557.5  1917.2   569.5 1918.75
#Mann= 3 ,-1,0
       0      .1       0   271.4    .045       0   285.2      .1       0
Bank Sta=271.4,285.2
XS Rating Curve= 0 ,0
Exp/Cntr(USF)=0,0
Exp/Cntr=0.3,0.1

Type RM Length L Ch R = 1 ,14374   ,263.7,267.8,271.1
XS GIS Cut Line= 3
2208239.14204527683833.7164396912208560.14771305683880.287210147
2208869.51068822683933.510947811
#Sta/Elev= 30
       0  1947.2    17.2 1937.23    25.3 1934.08    45.5 1929.22    65.7 1926.23
      98 1917.91   110.2 1913.63   126.3 1910.37   170.8 1895.55   215.3 1891.09
   243.6 1890.11   257.2 1883.34   263.8 1881.09   267.8 1880.98   271.8 1881.42
   275.9 1883.28     288 1889.52   300.1  1891.4   312.3 1890.16   340.6  1889.5
   353.2 1893.45     365 1891.49   413.7 1891.04   454.3 1890.82   490.8 1892.35
   535.4 1899.72   551.7 1900.64   567.6 1899.92   580.1 1901.09   638.3 1913.86
#Mann= 5 ,-1,0
       0      .1       0   257.2    .045       0   275.9      .1       0
  464.37    .025       0  544.37      .1       0
Bank Sta=257.2,275.9
XS Rating Curve= 0 ,0
Exp/Cntr(USF)=0,0
Exp/Cntr=0.3,0.1

Type RM Length L Ch R = 1 ,14106   ,182.9,183.3,183.4
XS GIS Cut Line= 3
2208162.56773636684002.8921312442208574.29651391684183.177047501
2208832.11040091684281.283216892
#Sta/Elev= 30
       0 1987.89    19.2 1980.65    36.7 1975.23      76 1974.42    84.7 1969.37
   102.2 1955.39   119.7 1943.62   128.4 1938.92     159 1930.09   180.8 1925.79
   224.5 1909.16   241.9  1900.8   272.5 1888.12   294.3  1881.3   321.8 1875.12
   333.6  1874.1     338 1875.04   346.7 1879.65   355.2 1886.01   359.8 1887.91
   394.9 1886.41   498.6 1888.22   549.9 1891.12   626.1 1892.58   639.8 1893.52
   650.9 1895.42   665.5 1894.35   669.8 1895.01     704 1906.98   725.3 1913.03
#Mann= 5 ,-1,0
       0      .1       0   321.8    .045       0     338      .1       0
  539.47    .025       0  589.47      .1       0
Bank Sta=321.8,338
XS Rating Curve= 0 ,0
Exp/Cntr(USF)=0,0
Exp/Cntr=0.3,0.1

Type RM Length L Ch R = 1 ,13922   ,300.9,301.4,301.7
XS GIS Cut Line= 3
2208072.35797284684160.3616592712208508.13188804684354.292459229
 2208752.2565421684459.243245088
#Sta/Elev= 30
       0  1995.2     4.2 1992.74    15.6 1981.73    21.7 1977.41    41.4 1973.43
      61 1966.44    88.3 1966.67    94.4 1965.59   115.6 1956.86   174.9 1927.63
   227.7 1907.88   266.9 1897.22   288.3 1885.62     307 1879.06   327.7 1869.28
   336.5 1867.87   342.71869.569     358 1876.54   367.6  1882.5   371.9  1883.2
   398.2 1881.86   415.6 1879.41   586.1 1879.25   651.2 1880.82   658.9 1882.22
   668.6 1885.27   681.7 1886.84   690.4 1888.94   707.8 1895.12   742.7 1905.67
#Mann= 6 ,-1,0
       0      .1       0   327.7    .045       0   342.7      .1       0
     370     .03       0     470    .025       0  616.98      .1       0
Bank Sta=327.7,342.7
XS Rating Curve= 0 ,0
Exp/Cntr(USF)=0,0
Exp/Cntr=0.3,0.1

Type RM Length L Ch R = 1 ,13621   ,142.9,141.3,138.5
XS GIS Cut Line= 3
2208016.38399066684452.5137035492208275.37105241684580.681362091
2208471.60015721 684666.42110608
#Sta/Elev= 30
       0 1940.49    44.4 1921.63    62.2 1913.39    80.1 1906.21    89.9 1903.29
   110.8 1898.52   138.1 1890.88   174.8 1879.85   191.4 1872.56   206.3 1869.23
   224.3 1863.74   230.2 1862.81     245 1862.34   249.7 1862.69   254.1 1863.71
     272 1872.19     287 1871.38   320.2 1871.09   329.4 1869.66   337.9 1870.56
   364.1 1867.71   372.8 1865.74   381.5 1868.22   385.9 1868.51   410.1 1868.53
   442.6    1867   463.1 1868.04   481.9  1869.9     495 1870.37   503.1    1870
#Mann= 4 ,-1,0
       0      .1       0   224.3    .045       0   254.1      .1       0
  428.97    .025       0
Bank Sta=224.3,254.1
XS Rating Curve= 0 ,0
Exp/Cntr(USF)=0,0
Exp/Cntr=0.3,0.1