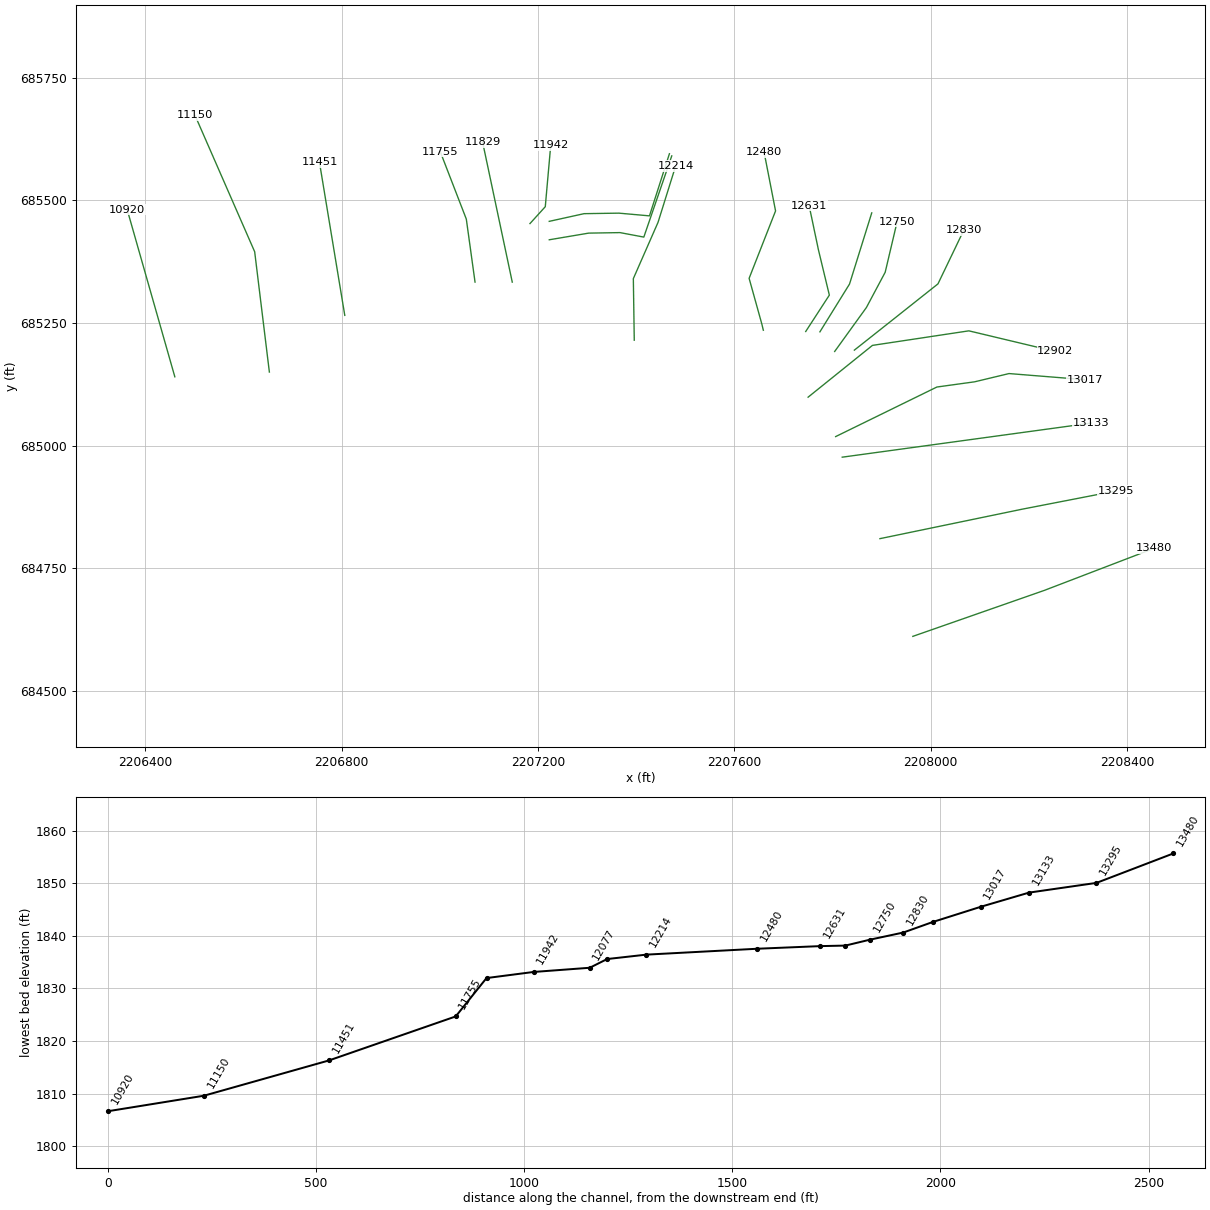
HEC-RAS study TENMILECK.prj: TENMILECK

--- TENMILECK.g01 (geometry) --- (continued)

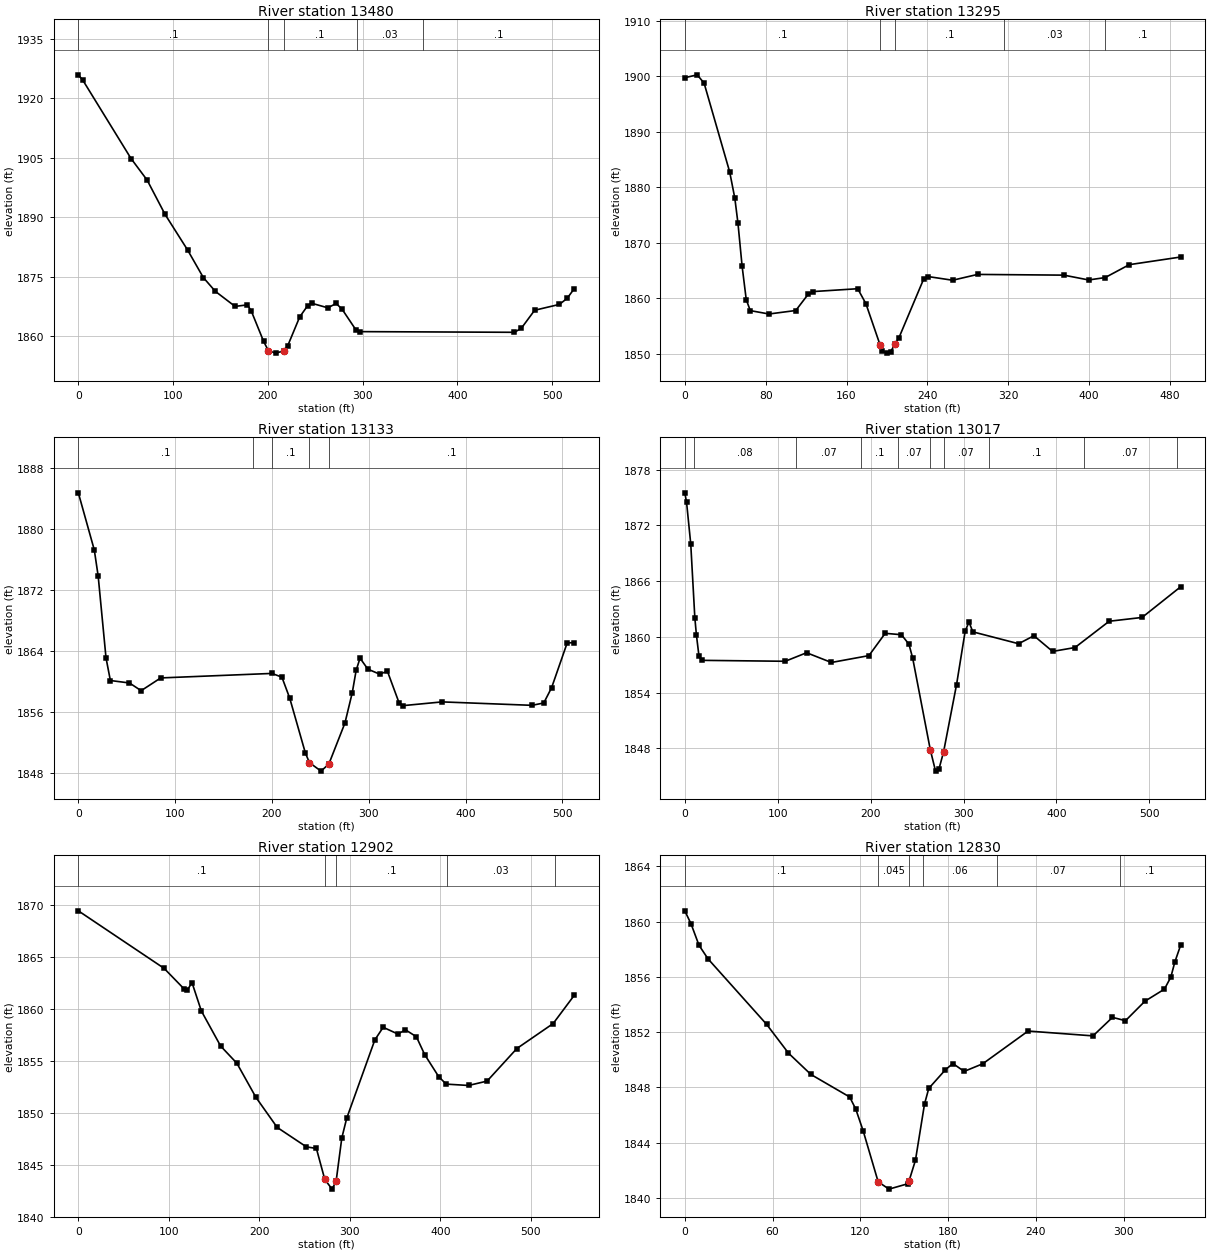
Type RM Length L Ch R = 1 ,13480   ,186.4,184.9,183.4
XS GIS Cut Line= 3
2207963.67994154684610.9566949882208231.50615215684704.651672956
2208455.13661843684790.391416946
#Sta/Elev= 30
       0 1925.86     4.8 1924.48    55.6 1904.76    72.6 1899.32    91.5 1890.68
   115.2 1881.74   131.9 1874.75   144.6 1871.27   165.4 1867.48   178.5 1867.87
   182.7  1866.2   195.5 1858.67   200.5 1856.33   208.2  1855.7   216.6 1856.25
   220.9 1857.53   233.6 1864.83   242.1  1867.7   246.3 1868.27   263.3 1867.12
   272.1 1868.23   278.4 1866.74     293 1861.53   297.3 1861.12   460.1 1860.95
   467.4 1861.95   481.5 1866.51   507.6 1867.98   515.8 1869.51   523.2 1871.92
#Mann= 5 ,-1,0
       0      .1       0   200.5    .045       0   216.6      .1       0
  293.74     .03       0  363.74      .1       0
Bank Sta=200.5,216.6
XS Rating Curve= 0 ,0
Exp/Cntr(USF)=0,0
Exp/Cntr=0.3,0.1

Type RM Length L Ch R = 1 ,13295   ,163,162.1,161.1
XS GIS Cut Line= 3
2207896.67822314684810.1467327832208186.60230591684870.252945065
 2208377.5279214684907.377370297
#Sta/Elev= 30
       0 1899.78    12.3  1900.3    19.1  1898.8    44.4 1882.79    49.5 1878.04
    52.6 1873.53    56.7 1865.78    60.8 1859.74    64.8 1857.76    83.3 1857.15
   109.8 1857.78     122 1860.69   127.3  1861.2   171.1 1861.71   179.2 1859.01
   193.41851.473   195.6 1850.48   199.7 1850.09   203.7 1850.37   207.8 1851.65
   211.9 1852.87   236.4 1863.48   240.5 1863.91     265 1863.24   289.7 1864.29
   375.1 1864.16   399.6 1863.29   415.9 1863.72   439.8 1866.05   490.6 1867.43
#Mann= 5 ,-1,0
       0      .1       0   193.4    .045       0   207.8      .1       0
  316.09     .03       0  416.09      .1       0
Bank Sta=193.4,207.8
XS Rating Curve= 0 ,0
Exp/Cntr(USF)=0,0
Exp/Cntr=0.3,0.1

Type RM Length L Ch R = 1 ,13133   ,116.1,116,115.8
XS GIS Cut Line= 2
2207819.83861712 684976.267044662208327.32155584685045.798441522
#Sta/Elev= 30
       0  1884.7    16.5 1877.21    20.5 1873.79    28.6 1863.07    33.1 1860.11
    52.8 1859.79    64.9 1858.78    85.1 1860.45     200 1861.04   210.3 1860.55
   218.4 1857.79   234.5 1850.63   238.71849.357   250.7 1848.24   258.81849.169
   275.4 1854.54     283 1858.53     287 1861.45     291 1863.04   299.1  1861.6
   311.2 1860.95   319.3 1861.32   331.3  1857.2   335.4 1856.82   375.8 1857.31
   468.7 1856.86   480.8 1857.17   488.9 1859.17     505 1865.04   512.2 1865.07
#Mann= 5 ,-1,0
       0      .1       0     180     .07       0     200      .1       0
   238.7    .045       0   258.8      .1       0
Bank Sta=238.7,258.8
XS Rating Curve= 0 ,0
Exp/Cntr(USF)=0,0
Exp/Cntr=0.3,0.1

Type RM Length L Ch R = 1 ,13017   ,115.1,114.8,115.7
XS GIS Cut Line= 5
2207806.43415781685018.2212437182208012.75951177685119.300626845
2208089.55019296685129.9025419972208159.72251636685146.720702151
2208313.52039178685134.345050387
#Sta/Elev= 30
       0 1875.51     1.9 1874.49     6.4 1870.01    10.8 1862.06    12.5  1860.2
    15.3  1857.9    18.5 1857.47   108.1 1857.37   131.1 1858.29   157.8 1857.24
   198.2 1857.98   215.7 1860.38   233.2 1860.23   241.3  1859.2   245.3  1857.7
   264.3 1847.82   269.9 1845.54   273.5 1845.74   278.51847.587   292.5 1854.85
   301.8 1860.62   305.9  1861.6     310 1860.54   359.3 1859.26   375.8 1860.12
   395.9 1858.43     420 1858.85   456.8 1861.68   492.2 1862.09   533.7 1865.39
#Mann= 10 ,-1,0
       0      .1       0      10     .08       0     120     .07       0
     190      .1       0  229.75     .07       0   264.3    .045       0
   278.5     .07       0  327.27      .1       0  429.43     .07       0
  529.43      .1       0
Bank Sta=264.3,278.5
XS Rating Curve= 0 ,0
Exp/Cntr(USF)=0,0
Exp/Cntr=0.3,0.1

Type RM Length L Ch R = 1 ,12902   ,64.5,71.4,79
XS GIS Cut Line= 4
2207750.32838804685098.5878252262207881.42214543685204.170137051
2208077.81526696685233.8166645172208253.75536991685191.792696473
#Sta/Elev= 30
       0  1869.4    94.8 1863.87   116.9 1861.89   120.5  1861.8   125.6  1862.5
   135.9 1859.78   157.2 1856.41   175.2 1854.75   196.2 1851.48   219.7 1848.59
     252 1846.72     263 1846.57   272.31843.589   280.3 1842.66   284.8 1843.41
   291.1 1847.58   296.5 1849.47   327.6    1857   336.8 1858.21   353.1 1857.56
   361.4 1857.97   373.5  1857.3   382.7 1855.58   398.2 1853.46   406.4 1852.75
   431.1 1852.62   451.6 1853.04   484.5 1856.17   524.6 1858.57   547.8 1861.27
#Mann= 5 ,-1,0
       0      .1       0   272.3    .045       0   284.8      .1       0
  406.94     .03       0  526.94     .07       0
Bank Sta=272.3,284.8
XS Rating Curve= 0 ,0
Exp/Cntr(USF)=0,0
Exp/Cntr=0.3,0.1

Type RM Length L Ch R = 1 ,12830   ,72.1,80.2,94.1
XS GIS Cut Line= 4
2207844.55473633685194.4954745612207917.61004034 685252.33092357
2208014.87371382685329.5503004852208067.55453694685439.177256528
#Sta/Elev= 30
       0 1860.78     4.3 1859.83     9.7 1858.29    15.9  1857.3    55.9 1852.57
    70.9 1850.48    86.2 1848.94   112.7 1847.31   116.9 1846.43     122 1844.84
   132.2 1841.17   139.6 1840.64   152.5 1841.03   153.4 1841.26   157.7 1842.73
   163.9  1846.8   166.8 1847.93   178.2 1849.28   183.3 1849.73     191 1849.16
   203.7 1849.71   234.7 1852.08   279.1 1851.73   292.4 1853.07   301.3 1852.83
   314.6 1854.24   327.9 1855.11   332.3 1855.98     335 1857.06     339 1858.29
#Mann= 6 ,-1,0
       0      .1       0   132.2    .045       0   153.4      .1       0
  163.18     .06       0  213.18     .07       0  297.37      .1       0
Bank Sta=132.2,153.4
XS Rating Curve= 0 ,0
Exp/Cntr(USF)=0,0
Exp/Cntr=0.3,0.1

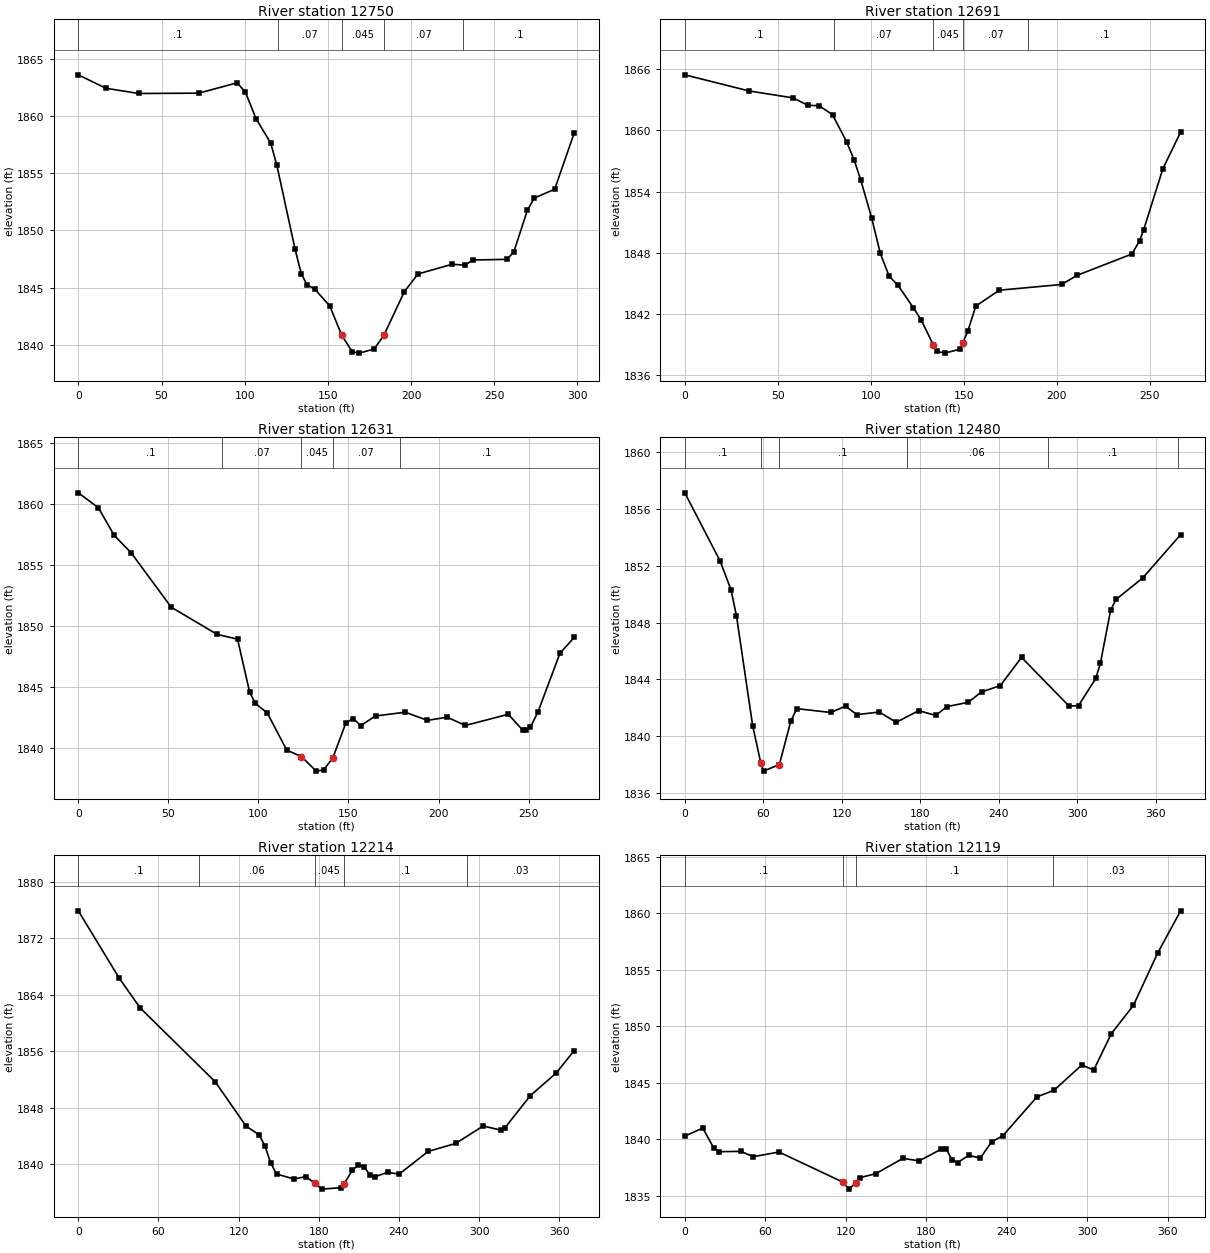
Type RM Length L Ch R = 1 ,12750   ,56.2,58.8,61.9
XS GIS Cut Line= 4
 2207804.4829252685191.7778734752207869.08872321685281.355837037
2207907.36453597685353.2679701082207931.72187137685456.496677259
#Sta/Elev= 30
       0 1863.58    16.5 1862.41    36.3 1861.95    72.4 1861.98    95.4 1862.88
   100.4 1862.08   106.8 1859.75   115.6 1857.63   119.3 1855.69   130.3 1848.33
     134 1846.22   137.4 1845.25     142 1844.89   151.1  1843.4   158.31840.842
   164.6 1839.41   168.8 1839.28   177.7 1839.63   183.6 1840.82   195.9 1844.64
   204.1 1846.19   224.7 1847.04   232.4 1846.96     237 1847.41   257.6 1847.47
   261.7 1848.11   269.9 1851.76     274 1852.82   286.3 1853.59     298 1858.49
#Mann= 5 ,-1,0
       0      .1       0   119.8     .07       0   158.3    .045       0
   183.6     .07       0  231.27      .1       0
Bank Sta=158.3,183.6
XS Rating Curve= 0 ,0
Exp/Cntr(USF)=0,0
Exp/Cntr=0.3,0.1

Type RM Length L Ch R = 1 ,12691   ,53.5,60.1,67.1
XS GIS Cut Line= 3
2207774.40558683685231.8083189072207834.71898876685329.237660488
2207879.95404021685474.221799744
#Sta/Elev= 30
       0 1865.45    34.5 1863.87    58.1 1863.19    66.2 1862.46    72.2 1862.42
    79.4 1861.54      87 1858.87      91 1857.11    94.6 1855.12   100.4 1851.44
   105.1 1847.93   109.8 1845.72   114.6  1844.8   122.9  1842.6   127.1  1841.4
   133.51838.989   135.5 1838.34   139.7 1838.16     148 1838.55   149.41839.153
   152.2 1840.36   156.4 1842.77     169 1844.33   202.5 1844.89   210.9 1845.79
   240.3 1847.88   244.4 1849.16   246.6 1850.24     257 1856.26   266.5 1859.83
#Mann= 5 ,-1,0
       0      .1       0      80     .07       0   133.5    .045       0
   149.4     .07       0  184.59      .1       0
Bank Sta=133.5,149.4
XS Rating Curve= 0 ,0
Exp/Cntr(USF)=0,0
Exp/Cntr=0.3,0.1

Type RM Length L Ch R = 1 ,12631   ,150.9,151.4,151.7
XS GIS Cut Line= 4
2207745.49192188  685232.50493872207793.59417967685306.631269546
2207771.36391728685398.9815739192207752.42970225685489.001170862
#Sta/Elev= 30
       0 1860.92    11.1  1859.7    19.9 1857.43    29.4 1855.98    51.6 1851.52
    77.1 1849.29    88.4  1848.9    95.1 1844.56    98.3 1843.62   104.9 1842.84
   115.7 1839.79   123.9 1839.25   132.1 1838.06   136.2 1838.16   141.31839.143
   148.6 1842.04   152.7 1842.37   156.8  1841.8     165 1842.59   181.5  1842.9
   193.8 1842.23   204.8 1842.49   214.9 1841.81   238.7 1842.73   246.9  1841.4
   248.7 1841.46     251 1841.68   255.1 1842.88   267.4 1847.74   275.3 1849.04
#Mann= 5 ,-1,0
       0      .1       0      80     .07       0   123.9    .045       0
   141.3     .07       0  178.37      .1       0
Bank Sta=123.9,141.3
XS Rating Curve= 0 ,0
Exp/Cntr(USF)=0,0
Exp/Cntr=0.3,0.1

Type RM Length L Ch R = 1 ,12480   ,275.4,266.4,256.4
XS GIS Cut Line= 5
 2207659.1163043685235.0374466822207656.12058024685247.519630266
2207630.15763838685340.8863634742207684.03516211685478.309312164
2207660.74823053685597.665192283
#Sta/Elev= 30
       0 1857.11      27 1852.32    35.3  1850.3    39.5 1848.47    51.9 1840.73
    58.21838.097    60.2 1837.56    72.31838.024      81 1841.06    85.6 1841.95
   111.5 1841.68   122.9 1842.12   131.5 1841.53   148.7 1841.71   161.6 1840.99
   178.8 1841.81   191.8 1841.47   200.3 1842.09   216.5 1842.39   226.8 1843.12
   241.2 1843.57   257.4 1845.55   293.8 1842.12     301 1842.17   314.2 1844.08
   317.7 1845.15   325.5 1848.87   329.6 1849.62   349.9 1851.12     379 1854.17
#Mann= 6 ,-1,0
       0      .1       0    58.2    .045       0    72.3      .1       0
  169.75     .06       0  277.35      .1       0  377.35     .03       0
Bank Sta=58.2,72.3
XS Rating Curve= 0 ,0
Exp/Cntr(USF)=0,0
Exp/Cntr=0.3,0.1

Type RM Length L Ch R = 1 ,12214   ,102.5,94.4,80.1
XS GIS Cut Line= 4
2207396.19091917685214.742803476 2207394.3083454685340.307854729
 2207444.6226622685455.0374566362207480.46395142685569.801991126
#Sta/Elev= 30
       0 1875.86    30.4 1866.38    46.4 1862.08   102.4 1851.66   125.6 1845.35
   135.3 1844.14   139.8  1842.5     144  1840.1   148.4 1838.58   161.5 1837.87
   170.2 1838.22   176.81837.303   182.3 1836.44   196.4 1836.64     1991837.213
   205.1 1839.12   209.5 1839.84   213.9 1839.63   218.3 1838.41   221.8 1838.18
   231.4 1838.82   240.1 1838.56   261.8 1841.78   282.4 1842.91     303 1845.38
   316.1 1844.81   319.3 1845.13   338.4  1849.7   357.6 1852.87   371.1 1856.06
#Mann= 5 ,-1,0
       0      .1       0      90     .06       0   176.8    .045       0
     199      .1       0  290.86     .03       0
Bank Sta=176.8,199
XS Rating Curve= 0 ,0
Exp/Cntr(USF)=0,0
Exp/Cntr=0.3,0.1

Type RM Length L Ch R = 1 ,12119   ,46.1,41.8,40.8
XS GIS Cut Line= 5
2207222.99999915 685419.476106972207303.37920596685433.046622404
2207367.05623992685434.0905082072207415.65663716685424.938582769
2207472.56019095685590.461986402
#Sta/Elev= 30
       0 1840.29    13.4    1841    21.5 1839.25    25.5 1838.91    41.8 1838.94
    51.1 1838.47    70.2 1838.88   117.9 1836.22   122.3  1835.6     1281836.184
   130.3 1836.61   142.3 1836.96   162.6 1838.32   174.8  1838.1   191.1 1839.13
   194.9 1839.16   199.1  1838.2   203.4 1837.95   211.8 1838.59   220.3 1838.34
   228.7 1839.77   237.2 1840.33   262.6 1843.76   275.3 1844.34     296 1846.58
   304.9 1846.13     318 1849.34   334.5 1851.85   352.6 1856.48   369.7 1860.21
#Mann= 4 ,-1,0
       0      .1       0   117.9    .045       0     128      .1       0
  274.66     .03       0
Bank Sta=117.9,128
XS Rating Curve= 0 ,0
Exp/Cntr(USF)=0,0
Exp/Cntr=0.3,0.1

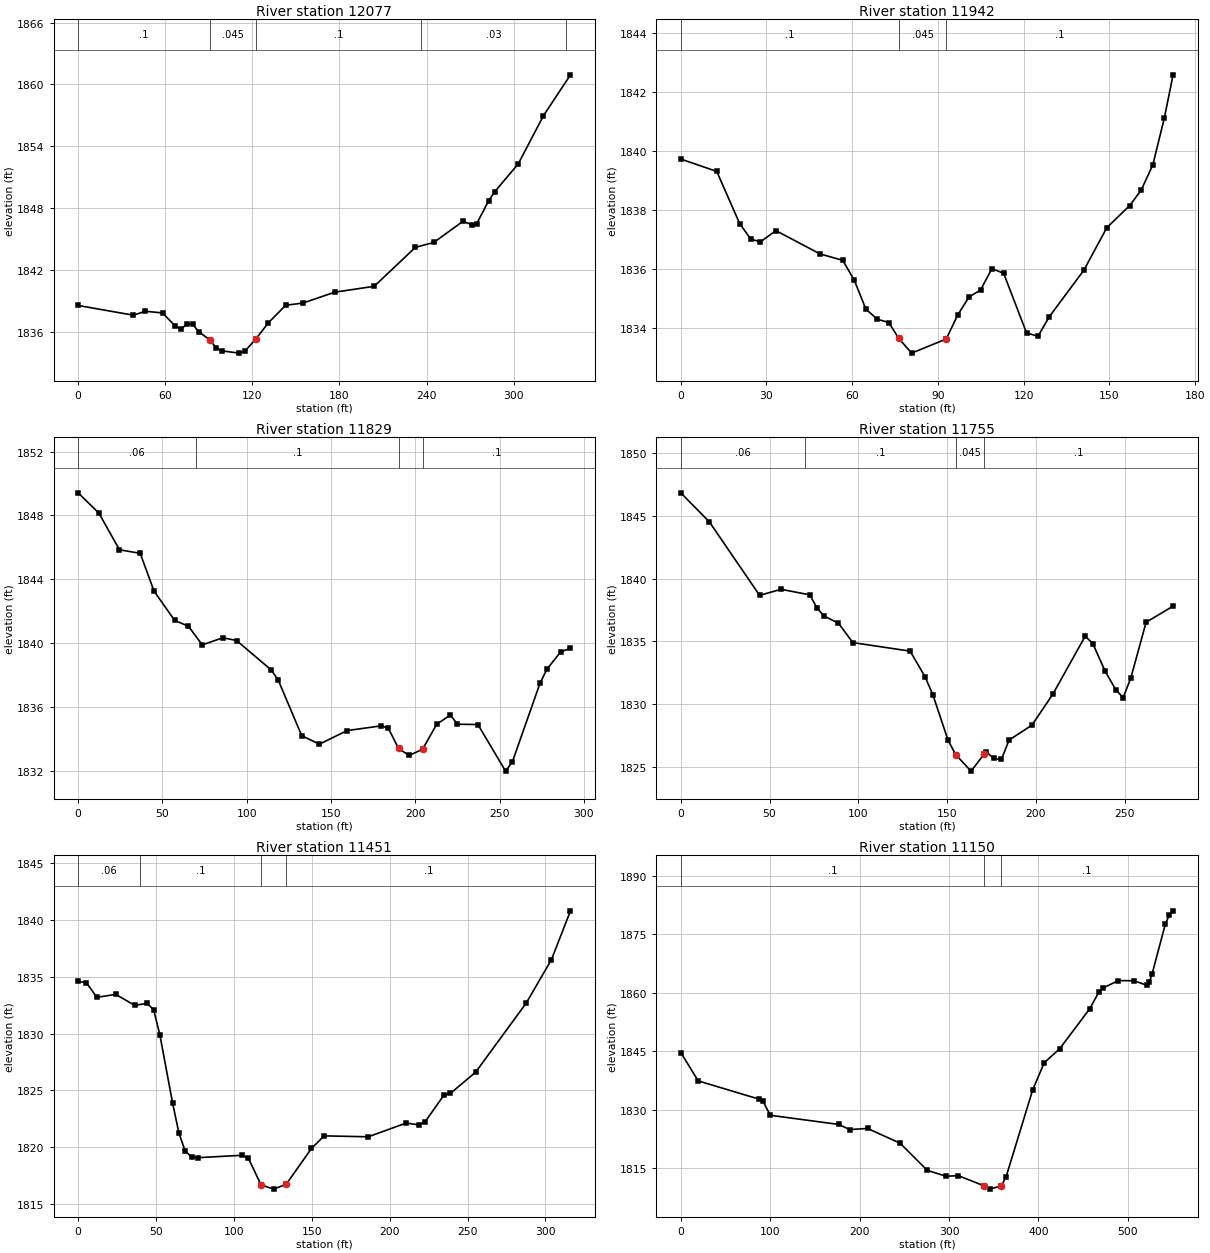
Type RM Length L Ch R = 1 ,12077   ,110.5,135,155.4
XS GIS Cut Line= 5
2207222.99999915685457.0559958652207293.98423373685472.714282905
2207364.96846831685473.7581687082207427.14764024685468.221561883
2207467.80294683685594.890682901
#Sta/Elev= 30
       0 1838.56      38 1837.62    46.3    1838    58.1 1837.84    66.7 1836.59
    70.8 1836.25    74.9 1836.78    78.9 1836.74    82.9 1836.03    90.9  1835.2
      95 1834.45    98.9 1834.16   110.9 1833.94   114.9 1834.13   122.6 1835.35
   130.9 1836.86   142.9 1838.58   154.9  1838.8   176.7 1839.85   203.9 1840.42
   232.3  1844.2   244.9 1844.67   264.9 1846.71   271.3  1846.4   274.5 1846.49
   282.7 1848.71   286.9 1849.59   303.1 1852.29   320.5 1856.97   339.1 1860.93
#Mann= 5 ,-1,0
       0      .1       0    90.9    .045       0   122.6      .1       0
  236.11     .03       0  336.11      .1       0
Bank Sta=90.9,122.6
XS Rating Curve= 0 ,0
Exp/Cntr(USF)=0,0
Exp/Cntr=0.3,0.1

Type RM Length L Ch R = 1 ,11942   ,109.3,113,116.6
XS GIS Cut Line= 3
2207183.74302547685452.5135615062207214.91646402685486.901611933
2207226.01173832685612.278211487
#Sta/Elev= 30
       0 1839.73    12.6 1839.31    20.6 1837.54    24.5 1837.01    27.9 1836.92
    33.3  1837.3    48.7 1836.51    56.7 1836.29    60.7 1835.62    64.8 1834.63
    68.8 1834.29    72.8 1834.18    76.31833.638    80.8 1833.14    92.9 1833.62
    96.9 1834.43   100.9 1835.05   104.9 1835.28   108.9 1836.01     113 1835.85
     121 1833.83     125 1833.71     129 1834.38   141.1 1835.96   149.1  1837.4
   157.1 1838.15   161.1 1838.67   165.2 1839.53   169.2 1841.11   172.3 1842.59
#Mann= 3 ,-1,0
       0      .1       0    76.3    .045       0    92.9      .1       0
Bank Sta=76.3,92.9
XS Rating Curve= 0 ,0
Exp/Cntr(USF)=0,0
Exp/Cntr=0.3,0.1

Type RM Length L Ch R = 1 ,11829   ,71.8,74,75.7
XS GIS Cut Line= 2
2207147.63671286685333.1749507192207087.15044283685618.876055973
#Sta/Elev= 30
       0 1849.42    12.3 1848.15    24.5 1845.85    36.8 1845.63      45 1843.26
    57.2 1841.43    65.4 1841.06    73.6 1839.89    85.9 1840.34      94 1840.16
   114.5 1838.32   118.6  1837.7   132.6  1834.2   143.1 1833.67   159.5 1834.52
   179.9 1834.82     184 1834.66     1901833.402   196.3 1832.96   204.31833.353
   212.6 1834.91   220.8  1835.5   224.9 1834.92   237.1  1834.9   253.5 1831.98
   257.6 1832.58   273.9 1837.48     278 1838.36   286.2 1839.46     292 1839.67
#Mann= 4 ,-1,0
       0     .06       0      70      .1       0     190    .045       0
   204.3      .1       0
Bank Sta=190,204.3
XS Rating Curve= 0 ,0
Exp/Cntr(USF)=0,0
Exp/Cntr=0.3,0.1

Type RM Length L Ch R = 1 ,11755   ,302.4,304.7,296.1
XS GIS Cut Line= 3
2207071.80312041 685333.200008322207054.05706177685461.597962045
2207000.81888583685599.390887994
#Sta/Elev= 30
       0 1846.83    16.1 1844.52    44.4 1838.67    56.5 1839.15    72.7 1838.71
    76.7 1837.67    80.7 1837.02    88.8 1836.46    96.9 1834.91   129.2 1834.23
   137.7 1832.16     142 1830.75   150.6 1827.12   154.9 1825.98   163.5 1824.68
     171 1826.06   172.1 1826.21   176.3 1825.69   180.6 1825.61   184.9 1827.15
   197.8 1828.34   209.5 1830.79   227.8 1835.42   232.1 1834.83     239 1832.64
   245.2 1831.11   249.2 1830.54   253.5  1832.1   262.1 1836.53   277.3 1837.81
#Mann= 4 ,-1,0
       0     .06       0      70      .1       0   154.9    .045       0
     171      .1       0
Bank Sta=154.9,171
XS Rating Curve= 0 ,0
Exp/Cntr(USF)=0,0
Exp/Cntr=0.3,0.1

Type RM Length L Ch R = 1 ,11451   ,289.7,300.3,298.2
XS GIS Cut Line= 2
 2206806.4469808685265.3580569822206754.89706462685577.235049871
#Sta/Elev= 30
       0  1834.6     5.3 1834.48      12 1833.19    24.1 1833.45    36.3 1832.49
    44.4 1832.66    48.5 1832.08    52.5 1829.87    60.6  1823.9    64.7 1821.23
    68.7 1819.66    72.8 1819.13    76.8 1819.07   105.2 1819.28   109.3 1819.02
   117.4 1816.68   125.5  1816.3   133.6 1816.73   149.8 1819.88   157.9 1820.99
   186.3 1820.91   210.6 1822.12   218.7 1821.96   222.8 1822.24   234.9 1824.59
     239 1824.73   255.2  1826.6   287.7 1832.69   303.9 1836.52   316.1 1840.81
#Mann= 4 ,-1,0
       0     .06       0      40      .1       0   117.4    .045       0
   133.6      .1       0
Bank Sta=117.4,133.6
XS Rating Curve= 0 ,0
Exp/Cntr(USF)=0,0
Exp/Cntr=0.3,0.1

Type RM Length L Ch R = 1 ,11150   ,229.9,230.6,224.8
XS GIS Cut Line= 3
2206652.83072123685149.7975342012206622.90102504685395.066898521
2206501.36549903685673.137002574
#Sta/Elev= 30
       0 1844.63    19.5 1837.35      88 1832.64    92.1 1832.07   100.1 1828.53
   176.7 1826.18   188.8 1824.87   208.9 1825.15   245.2 1821.38   275.6 1814.42
   296.3 1812.91   310.5 1813.03   338.9 1810.47   345.4 1809.59   358.5 1810.41
   363.8 1812.73   393.5 1834.99   406.5 1842.02   423.7 1845.58   457.3 1855.83
   467.7 1860.16     472 1861.16   489.5 1863.08     507 1863.03   521.1 1861.89
   524.2 1862.81   527.2 1864.86   541.9 1877.55   546.2 1879.84   550.6 1880.97
#Mann= 3 ,-1,0
       0      .1       0   338.9    .045       0   358.5      .1       0
Bank Sta=338.9,358.5
XS Rating Curve= 0 ,0
Exp/Cntr(USF)=0,0
Exp/Cntr=0.3,0.1

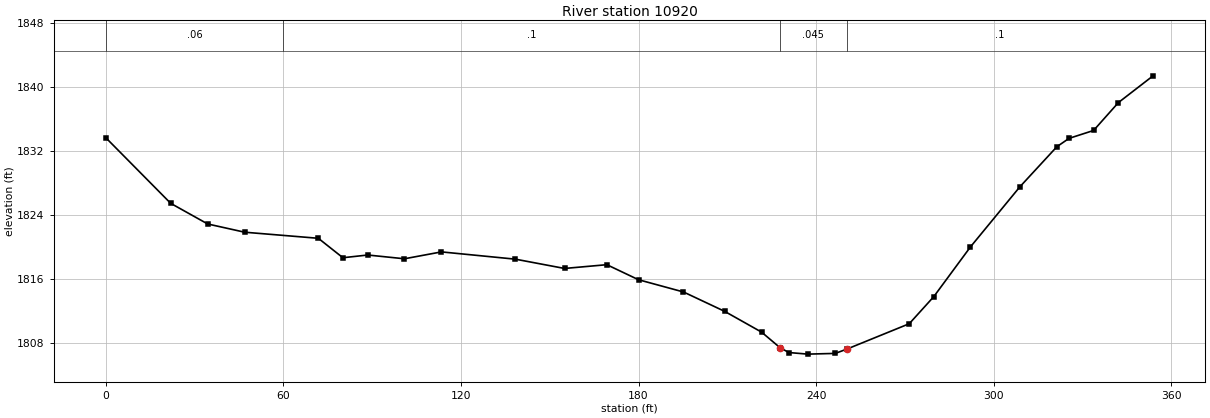
Type RM Length L Ch R = 1 ,10920   ,290.3,286.8,282.8
XS GIS Cut Line= 2
2206460.22858241685140.0969689862206363.32142212685480.433559714
#Sta/Elev= 30
       0 1833.68    21.9 1825.49    34.4 1822.91    46.9 1821.88    71.8 1821.12
    80.1 1818.69    88.5 1819.03   100.9 1818.56   113.4 1819.42   138.4 1818.51
     155 1817.35   169.3 1817.82     180 1815.94   195.2 1814.41   209.1 1811.99
   221.6 1809.39   227.81807.455   230.8 1806.84   237.2 1806.64   246.5 1806.73
   250.41807.266   271.5 1810.44   279.8 1813.83   292.2 1820.05   308.9 1827.56
   321.4 1832.57   325.5 1833.61   333.8  1834.6   342.2 1838.09   353.9 1841.43
#Mann= 4 ,-1,0
       0     .06       0      60      .1       0   227.8    .045       0
   250.4      .1       0
Bank Sta=227.8,250.4
XS Rating Curve= 0 ,0
Exp/Cntr(USF)=0,0
Exp/Cntr=0.3,0.1