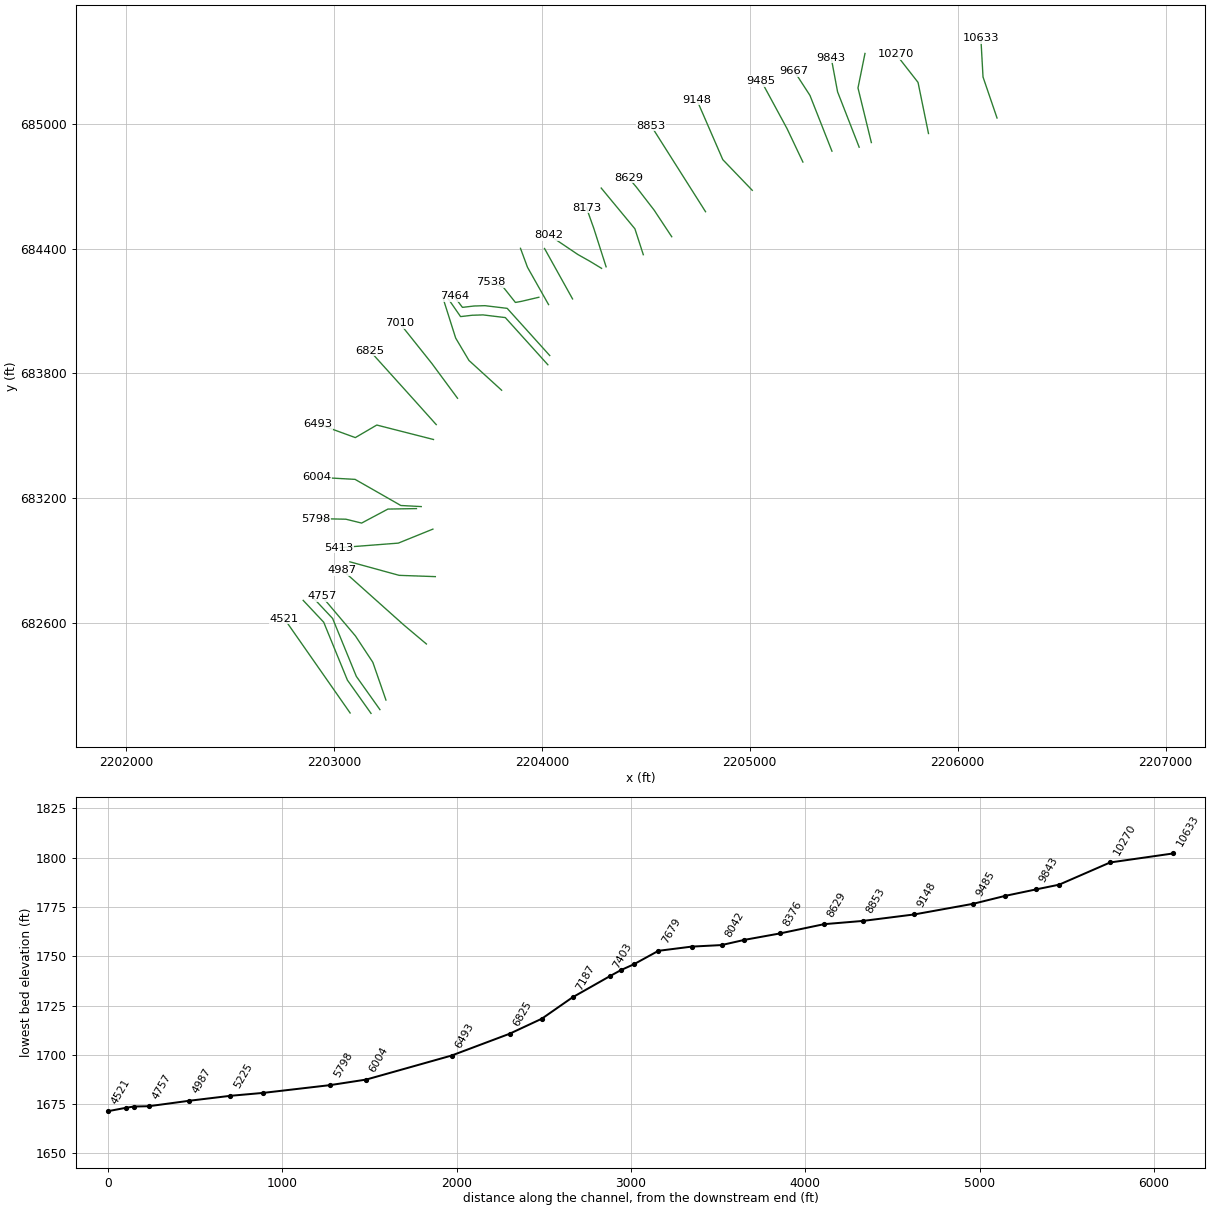
HEC-RAS study TENMILECK.prj: TENMILECK

--- TENMILECK.g01 (geometry) --- (continued)

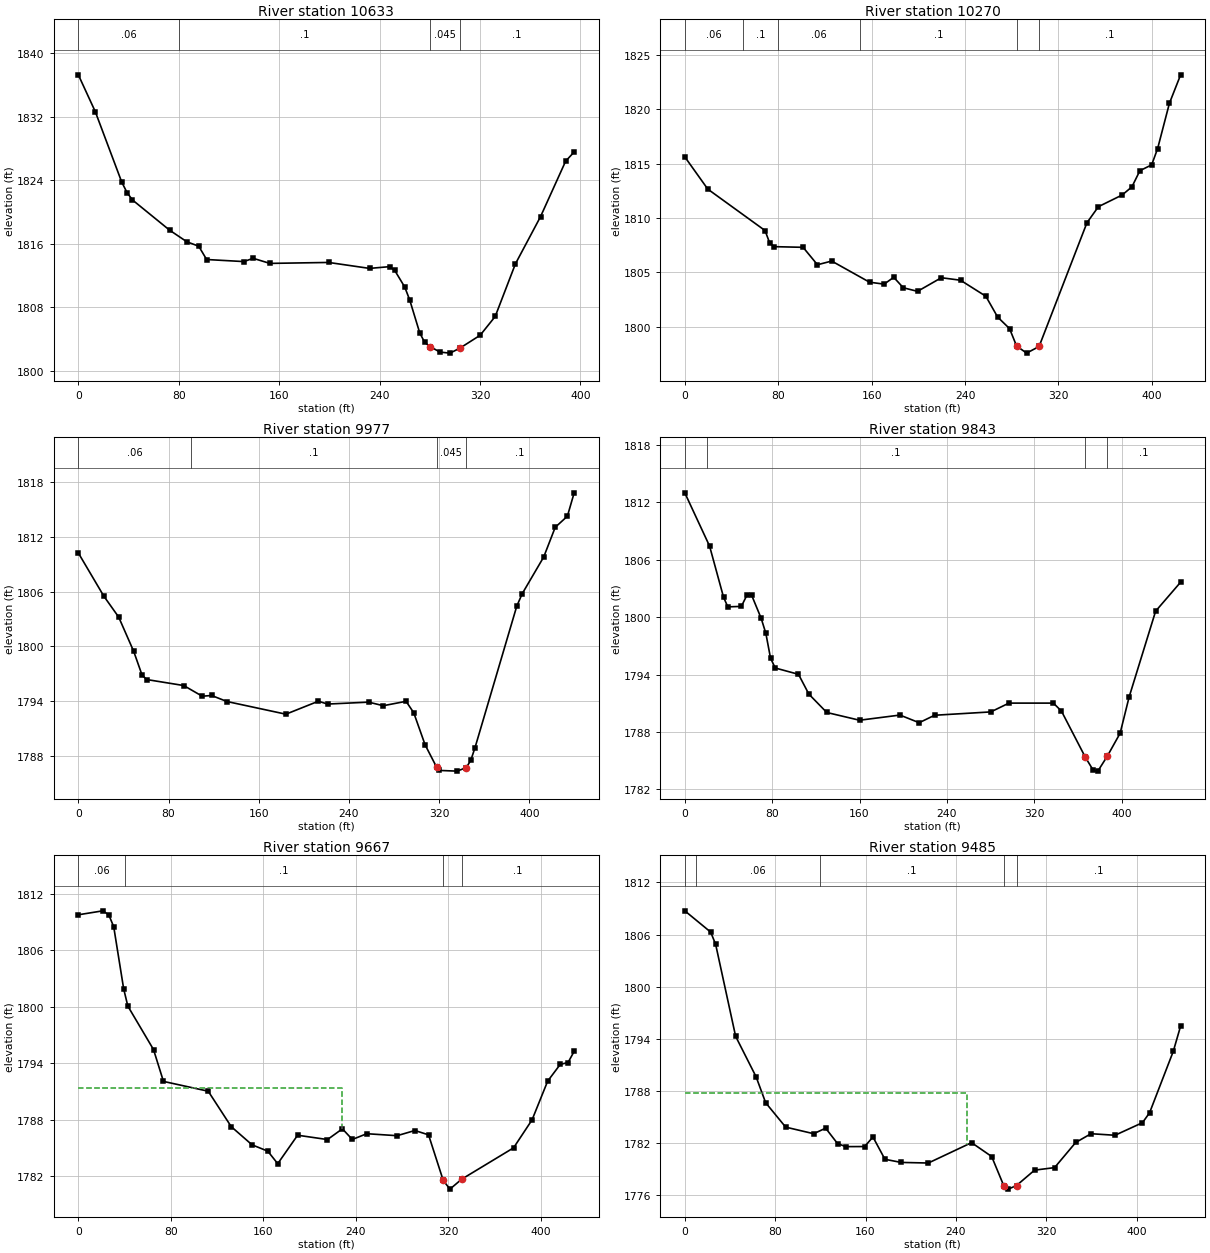
Type RM Length L Ch R = 1 ,10633   ,352,363.4,370
XS GIS Cut Line= 3
2206189.16078902685028.4156281322206121.76624739 685225.93420103
2206111.43177794685411.954651061
#Sta/Elev= 30
       0 1837.28    13.5 1832.64    34.6 1823.75    38.8 1822.44    43.1 1821.51
    72.7  1817.7    86.5 1816.23    95.9 1815.68   102.2    1814   131.8 1813.74
   139.3 1814.15   152.6 1813.51   199.4 1813.63     232 1812.88     248  1813.1
     252 1812.64     260 1810.54     264  1808.9     272 1804.74     276 1803.54
   280.11803.034   288.1 1802.33   296.1  1802.2   304.1 1802.84   320.1 1804.45
   332.1 1806.82   348.2 1813.45   368.2  1819.4   388.2 1826.39     395 1827.56
#Mann= 4 ,-1,0
       0     .06       0      80      .1       0   280.1    .045       0
   304.1      .1       0
Bank Sta=280.1,304.1
XS Rating Curve= 0 ,0
Exp/Cntr(USF)=0,0
Exp/Cntr=0.3,0.1

Type RM Length L Ch R = 1 ,10270   ,301.6,292.1,275
XS GIS Cut Line= 3
2205859.55767075684953.8937911652205809.24866724685199.887189849
2205702.54034075685336.752217306
#Sta/Elev= 30
       0 1815.61    19.7 1812.65    68.7 1808.85    72.8 1807.68    76.8 1807.37
   101.3 1807.31   113.6 1805.71   125.8 1806.05   158.2 1804.11   170.7 1803.93
   178.9 1804.56   187.1  1803.6   199.3 1803.27   219.7 1804.52   236.1 1804.29
   257.8 1802.82   267.9 1800.91   278.1 1799.85   284.1 1798.26   292.7  1797.6
   303.4 1798.21   344.4 1809.57   354.2 1811.04   374.5 1812.11   382.9 1812.86
   389.7 1814.34   399.8 1814.88   404.9 1816.37     415 1820.53   424.6 1823.14
#Mann= 6 ,-1,0
       0     .06       0      50      .1       0      80     .06       0
     150      .1       0   284.1    .045       0   303.4      .1       0
Bank Sta=284.1,303.4
XS Rating Curve= 0 ,0
Exp/Cntr(USF)=0,0
Exp/Cntr=0.3,0.1

Type RM Length L Ch R = 1 ,9977    ,127,134.5,139.8
XS GIS Cut Line= 3
2205584.68118219684910.3797010862205520.44026184685173.210108225
2205554.07658215685339.071963534
#Sta/Elev= 30
       0 1810.25    22.6 1805.52    35.8 1803.22    49.1 1799.47    56.4 1796.91
    60.5 1796.38    93.5 1795.72   109.9 1794.55   118.2 1794.63   131.8 1793.97
   184.1 1792.58   212.9    1794   221.1 1793.69   257.5  1793.9   270.5 1793.51
   290.7 1793.99   297.5 1792.74   307.6 1789.22   317.8 1786.77   319.5 1786.42
   335.8 1786.34     344 1786.71   348.1 1787.52   351.8 1788.89   388.9 1804.42
   393.7 1805.78   412.8 1809.81     423 1813.06   433.8 1814.28   439.8 1816.84
#Mann= 4 ,-1,0
       0     .06       0     100      .1       0   317.8    .045       0
     344      .1       0
Bank Sta=317.8,344
XS Rating Curve= 0 ,0
Exp/Cntr(USF)=0,0
Exp/Cntr=0.3,0.1

Type RM Length L Ch R = 1 ,9843    ,167.3,175.8,177.7
XS GIS Cut Line= 3
2205526.13140558684888.0729650632205422.34674845  685154.2795846
2205391.34334011685319.631095746
#Sta/Elev= 30
       0 1812.99    22.7 1807.42    35.5 1802.07    39.4 1801.07    51.8 1801.12
      57 1802.32    61.3 1802.26    69.9 1799.88    74.2 1798.31    78.5 1795.71
    82.8 1794.68   104.1 1794.02   113.6 1791.95     130 1790.03     160 1789.22
     197 1789.76   214.6 1788.96   228.7 1789.74   280.2 1790.09   296.8 1791.01
   337.5 1791.01   344.9 1790.17   366.8 1785.34   374.1 1783.97   378.2  1783.9
   386.8 1785.45   398.6 1787.86   406.8 1791.63   431.1 1800.62     454 1803.65
#Mann= 4 ,-1,0
       0     .06       0      20      .1       0   366.8    .045       0
   386.8      .1       0
Bank Sta=366.8,386.8
XS Rating Curve= 0 ,0
Exp/Cntr(USF)=0,0
Exp/Cntr=0.3,0.1

Type RM Length L Ch R = 1 ,9667    ,182.9,182.7,181.6
XS GIS Cut Line= 3
2205395.24416763684868.735087482 2205289.4257463685137.343637835
2205213.30861646 685254.80043095
#Sta/Elev= 30
       0 1809.75    21.2 1810.17    26.3 1809.75    30.6 1808.48    39.2 1801.89
    42.8 1800.06      65 1795.45    73.6 1792.07   112.3 1791.03   132.2 1787.27
   150.2 1785.34   163.8 1784.67   172.4 1783.34   189.6 1786.36   215.4  1785.9
   228.3 1787.04   236.9 1785.91   249.4 1786.52   275.6 1786.31     291 1786.86
   302.8  1786.4   315.5 1781.56   321.3 1780.64   331.4 1781.69   376.3 1785.02
   392.3 1787.99   405.8  1792.1   416.7 1793.88   423.4 1794.07   428.7 1795.26
#Mann= 4 ,-1,0
       0     .06       0      40      .1       0   315.5    .045       0
   331.4      .1       0
#XS Ineff= 2 , 0
          227.89 1791.38
Permanent Ineff=
       F       F
Bank Sta=315.5,331.4
XS Rating Curve= 0 ,0
Exp/Cntr(USF)=0,0
Exp/Cntr=0.3,0.1

Type RM Length L Ch R = 1 ,9485    ,337.6,337,336.2
XS GIS Cut Line= 3
2205255.51664587684816.4997119432205179.31298228 684977.25812555
2205055.09057176685206.913002131
#Sta/Elev= 30
       0 1808.73    22.9 1806.28    27.3 1804.87      45 1794.26    63.1  1789.6
    71.6  1786.6    89.3 1783.79   114.1 1783.03   124.7 1783.67   135.2  1781.9
   142.4 1781.54   159.2 1781.55   166.6 1782.65   177.2 1780.08   191.5 1779.72
   215.6 1779.65   253.9    1782   271.7  1780.4   282.4 1777.04   286.4 1776.64
   293.71777.055   309.7 1778.83   327.4 1779.12   346.1 1782.02   359.7 1783.03
   380.9 1782.85   405.2  1784.3   411.5 1785.44   432.5 1792.53     439 1795.45
#Mann= 5 ,-1,0
       0      .1       0      10     .06       0     120      .1       0
   282.4    .045       0   293.7      .1       0
#XS Ineff= 2 , 0
          249.58  1787.7
Permanent Ineff=
       F       F
Bank Sta=282.4,293.7
XS Rating Curve= 0 ,0
Exp/Cntr(USF)=0,0
Exp/Cntr=0.3,0.1

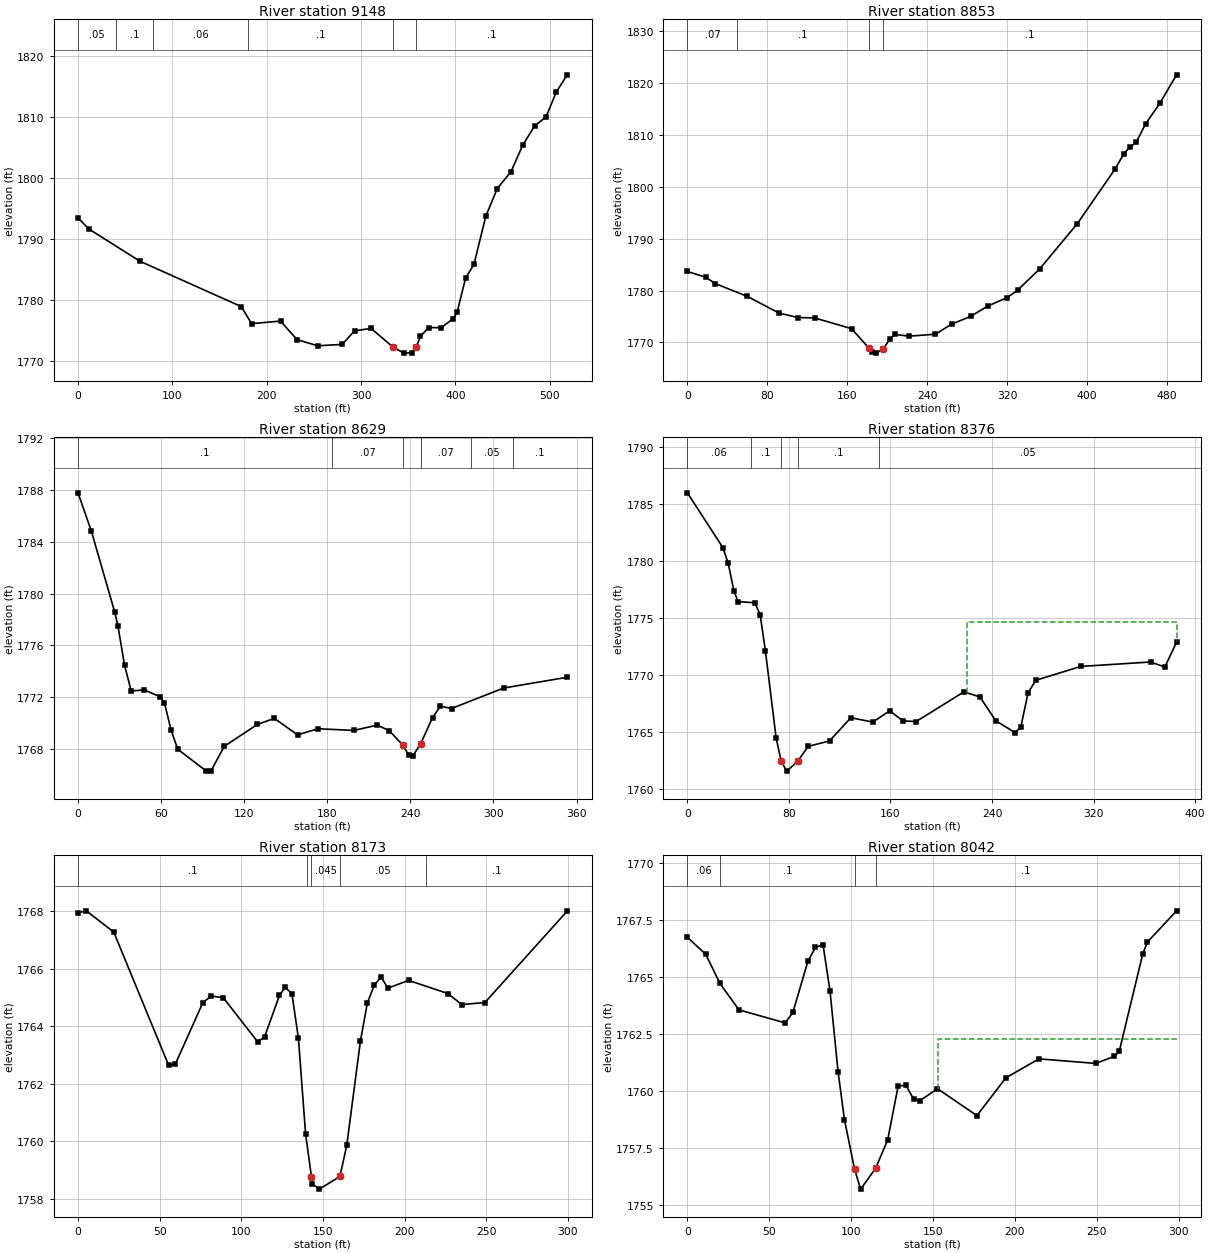
Type RM Length L Ch R = 1 ,9148    ,292.9,294.9,297.8
XS GIS Cut Line= 3
2205012.01870317  684680.40460132204870.23757746684828.140246532
2204745.39050451685115.847819641
#Sta/Elev= 30
       0 1793.48    11.3 1791.67    65.5 1786.36     173  1778.9     184 1776.09
   214.6 1776.52   232.1 1773.47   253.9 1772.46     280 1772.68   293.1 1774.92
   310.6 1775.31   333.7 1772.26   345.4 1771.25   354.1 1771.32   358.5 1772.31
   362.9    1774   371.6 1775.46   384.7 1775.42   397.8 1776.93   401.7 1777.94
   410.8 1783.61   419.6 1785.82   432.1 1793.71   444.3  1798.3   458.8 1801.05
   471.2 1805.39   483.8 1808.57     496 1810.06   506.8 1814.13   518.4 1816.98
#Mann= 6 ,-1,0
       0     .05       0      40      .1       0      80     .06       0
     180      .1       0   333.7    .045       0   358.5      .1       0
Bank Sta=333.7,358.5
XS Rating Curve= 0 ,0
Exp/Cntr(USF)=0,0
Exp/Cntr=0.3,0.1

Type RM Length L Ch R = 1 ,8853    ,221.6,223.5,223.5
XS GIS Cut Line= 2
2204787.25289796684577.6209619532204525.31859285 684991.40810402
#Sta/Elev= 30
       0  1783.7    18.4 1782.58    27.9 1781.36    59.9  1778.9    91.8 1775.67
   110.5 1774.82   127.3 1774.74   164.3 1772.67   181.61768.938   184.5 1768.25
   188.8 1767.95   196.1 1768.76     203 1770.76   207.7 1771.56     222 1771.22
   248.3  1771.6   264.6 1773.55   283.5 1775.03   300.5 1777.01   319.9 1778.64
   330.9 1780.14   352.7  1784.2   390.4 1792.93   428.1 1803.44   436.8 1806.34
   442.6 1807.64   449.2 1808.57   458.7 1812.17   472.9  1816.1   489.7 1821.62
#Mann= 4 ,-1,0
       0     .07       0      50      .1       0   181.6    .045       0
   196.1      .1       0
Bank Sta=181.6,196.1
XS Rating Curve= 0 ,0
Exp/Cntr(USF)=0,0
Exp/Cntr=0.3,0.1

Type RM Length L Ch R = 1 ,8629    ,255.2,253.1,247.8
XS GIS Cut Line= 4
2204624.62029178684457.1135322322204540.01480891684585.171701129
2204454.03390212684696.6787474582204416.25202132 684741.89393028
#Sta/Elev= 30
       0 1787.77     9.7  1784.8    26.4 1778.61    28.8 1777.52    33.6 1774.47
    38.4 1772.49      48 1772.56    58.9 1772.05    62.4 1771.58    67.2 1769.47
      72 1767.99    92.7  1766.3      96 1766.31   105.6 1768.21   129.5  1769.9
   141.8 1770.37   158.5  1769.1   173.3 1769.57   199.1 1769.44   216.1 1769.85
   224.7 1769.42   234.71768.292   238.9 1767.51   241.8 1767.48   247.5 1768.43
     256 1770.43   261.7 1771.31   269.7 1771.13   307.3 1772.71   353.2 1773.54
#Mann= 6 ,-1,0
       0      .1       0  183.48     .07       0   234.7    .045       0
   247.5     .07       0  283.48     .05       0  314.29      .1       0
Bank Sta=234.7,247.5
XS Rating Curve= 0 ,0
Exp/Cntr(USF)=0,0
Exp/Cntr=0.3,0.1

Type RM Length L Ch R = 1 ,8376    ,203.1,203.1,204.4
XS GIS Cut Line= 3
2204487.95444933684370.673211293 2204447.5457343684495.323823764
2204285.50020284684691.336240245
#Sta/Elev= 30
       0 1786.02    27.9 1781.22    32.1 1779.86    36.7 1777.39    39.9 1776.47
    53.1 1776.37    57.3 1775.33    61.5 1772.12    69.9 1764.51    73.91762.463
    78.3 1761.59    86.81762.439    95.1 1763.76     112 1764.24   128.8 1766.28
   146.1 1765.89   159.4 1766.89   169.8    1766   180.2 1765.94   217.9 1768.55
   230.5  1768.1     243 1766.01     258 1764.98   262.6 1765.42   268.4 1768.45
   274.4 1769.56   309.9 1770.78   364.9 1771.17   376.2 1770.73   385.4 1772.92
#Mann= 5 ,-1,0
       0     .06       0      50      .1       0    73.9    .045       0
    86.8      .1       0  151.04     .05       0
#XS Ineff= 2 , 0
                          220.62         1774.68
Permanent Ineff=
       F       F
Bank Sta=73.9,86.8
XS Rating Curve= 0 ,0
Exp/Cntr(USF)=0,0
Exp/Cntr=0.3,0.1

Type RM Length L Ch R = 1 ,8173    ,121.4,131.3,140.3
XS GIS Cut Line= 3
2204309.04157487684312.3535625862204250.14073601684496.589907391
 2204214.5262753684596.584354757
#Sta/Elev= 30
       0 1767.95     5.1 1768.02    21.9 1767.28    55.5 1762.65    59.7  1762.7
    76.5 1764.83    81.7 1765.06    89.1 1764.99   110.1 1763.46   114.3 1763.64
   123.4 1765.08   126.9 1765.36     131 1765.14     135 1763.59   139.4 1760.25
     1431758.767   143.6 1758.52   147.8 1758.34   160.4 1758.78   164.6 1759.86
     173  1763.5   177.2 1764.81   181.4 1765.43   185.6 1765.72   189.8 1765.33
   202.5  1765.6   226.7 1765.14     235 1764.76   249.2 1764.83   299.6 1768.01
#Mann= 5 ,-1,0
       0      .1       0     140     .05       0     143    .045       0
   160.4     .05       0  213.42      .1       0
Bank Sta=143,160.4
XS Rating Curve= 0 ,0
Exp/Cntr(USF)=0,0
Exp/Cntr=0.3,0.1

Type RM Length L Ch R = 1 ,8042    ,177.1,172.1,166.2
XS GIS Cut Line= 4
2204287.26089115684304.9459414422204230.96371871684339.064408115
2204173.28108813684371.5412625532204035.15244851684464.762874443
#Sta/Elev= 30
       0 1766.76    11.2 1766.01    19.9 1764.73    31.5 1763.57    59.7    1763
    64.4 1763.46    73.6 1765.71    78.2 1766.31    82.8 1766.44    87.1 1764.39
      92 1760.86    95.9 1758.75   102.11756.565   105.8  1755.7   114.9 1756.61
   122.3 1757.86   128.7 1760.23   133.4 1760.26   138.2 1759.65   142.1 1759.59
   152.7 1760.11   176.8 1758.93   194.5 1760.59   214.7 1761.42   249.3 1761.22
   260.8 1761.53   263.7 1761.75   278.1 1766.04   280.9 1766.55   298.7 1767.92
#Mann= 4 ,-1,0
       0     .06       0      20      .1       0   102.1    .045       0
   114.9      .1       0
#XS Ineff= 2 , 0
                          152.79         1762.29
Permanent Ineff=
       F       F
Bank Sta=102.1,114.9
XS Rating Curve= 0 ,0
Exp/Cntr(USF)=0,0
Exp/Cntr=0.3,0.1

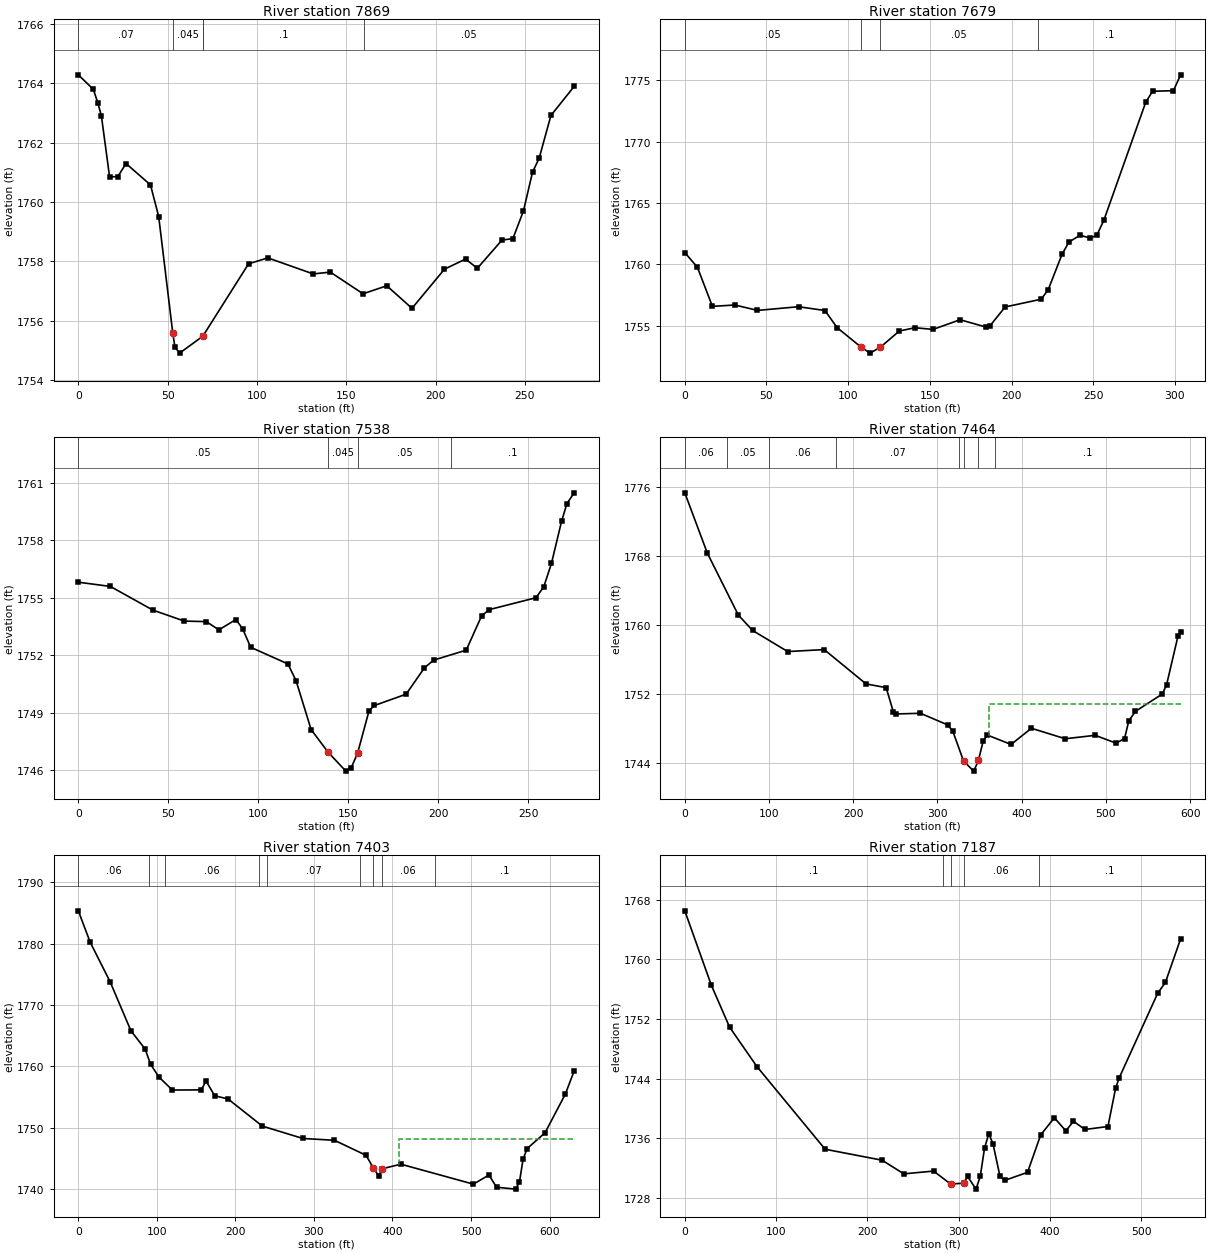
Type RM Length L Ch R = 1 ,7869    ,182.6,190.1,187.4
XS GIS Cut Line= 2
2204147.70333796684157.8728876042204012.83851169684400.545020148
#Sta/Elev= 30
       0 1764.29     8.4  1763.8    10.9 1763.35    12.9 1762.91    17.5 1760.85
    22.1 1760.86    26.7  1761.3    40.4 1760.58      45 1759.51    52.91755.572
    54.1 1755.11    56.7 1754.91    69.7 1755.48    95.3 1757.92   106.1 1758.12
   131.5 1757.58   141.1 1757.64   159.4 1756.91   172.7 1757.18   186.8 1756.42
     205 1757.74   216.8 1758.08   223.4 1757.77   237.2 1758.72   243.3 1758.77
   249.2  1759.7   254.3 1761.01     258 1761.48   264.6 1762.92   277.6  1763.9
#Mann= 5 ,-1,0
       0     .07       0    52.9    .045       0    69.7     .07       0
      70      .1       0     160     .05       0
Bank Sta=52.9,69.7
XS Rating Curve= 0 ,0
Exp/Cntr(USF)=0,0
Exp/Cntr=0.3,0.1

Type RM Length L Ch R = 1 ,7679    ,138.7,141.1,142.8
XS GIS Cut Line= 3
2204032.37723359684130.4554075162203930.93768901684310.134031812
2203897.29363451684401.303788344
#Sta/Elev= 30
       0 1760.97     7.7 1759.78    16.9 1756.59    30.7  1756.7    44.5 1756.26
    69.7 1756.56    85.8 1756.25    93.2 1754.86   107.8 1753.28   113.4 1752.78
   119.6 1753.25   131.3 1754.58   140.9 1754.85   151.9 1754.71   168.5  1755.5
   184.2 1754.91   186.9 1755.02   196.1 1756.54   218.1 1757.17   222.4 1757.93
   230.9 1760.83   235.2 1761.84     242 1762.38   248.2 1762.15   252.2 1762.38
   256.5  1763.6   282.1  1773.2   286.3 1774.11   299.1 1774.16   303.5 1775.45
#Mann= 4 ,-1,0
       0     .05       0   107.8    .045       0   119.6     .05       0
  216.34      .1       0
Bank Sta=107.8,119.6
XS Rating Curve= 0 ,0
Exp/Cntr(USF)=0,0
Exp/Cntr=0.3,0.1

Type RM Length L Ch R = 1 ,7538    ,62.6,73.8,83.6
XS GIS Cut Line= 5
2203985.51360894684165.7569310922203902.85381543684146.340201073
2203872.89657483684140.792563924 2203815.7559122684212.911846854
2203752.51284871684238.430977736
#Sta/Elev= 30
       0 1755.81    17.8 1755.59    41.5 1754.35    58.9 1753.78    71.2 1753.75
    78.1 1753.32    87.6 1753.86    91.3 1753.38    95.8 1752.41   116.5 1751.54
     121 1750.67   129.4 1748.11   138.9 1746.92   148.7 1745.94   151.6  1746.1
   155.2 1746.87   161.6  1749.1   164.6 1749.37   182.2 1749.96   192.4 1751.34
   197.5 1751.74   215.6 1752.26   224.2 1754.06   228.5 1754.38   254.4    1755
   258.7 1755.57     263  1756.8   268.7 1759.03   271.6 1759.92   275.6 1760.48
#Mann= 4 ,-1,0
       0     .05       0   138.9    .045       0   155.2     .05       0
  207.39      .1       0
Bank Sta=138.9,155.2
XS Rating Curve= 0 ,0
Exp/Cntr(USF)=0,0
Exp/Cntr=0.3,0.1

Type RM Length L Ch R = 1 ,7464    ,64.2,61.8,61.5
XS GIS Cut Line= 6
2204037.99622304683885.3192426062203833.31402735684112.413622945
2203726.14466583684125.3255942122203673.66499183684123.657843386
2203618.13154828684117.1070917492203578.23448012684170.466921802
#Sta/Elev= 30
       0 1775.33    26.7 1768.34    63.5 1761.14    80.5 1759.34   122.2 1756.89
   165.5 1757.12   215.2 1753.13   239.1  1752.7   247.5 1749.91   250.4 1749.64
   279.8 1749.72   312.3 1748.36   318.3 1747.62     331 1744.16   343.1    1743
   348.6 1744.25   354.3 1746.49   359.2 1747.19   387.4  1746.1   411.5 1747.98
   451.7 1746.76   487.3 1747.16     512 1746.25   522.1 1746.78   527.2 1748.85
     535 1749.94   567.1 1751.97   572.1 1753.06   585.5 1758.66   588.7 1759.21
#Mann= 8 ,-1,0
       0     .06       0      50     .05       0     100     .06       0
     180     .07       0  325.72     .05       0     331    .045       0
   348.6     .05       0  368.57      .1       0
#XS Ineff= 2 , 0
                          361.69          1750.8
Permanent Ineff=
       F       F
Bank Sta=331,348.6
XS Rating Curve= 0 ,0
Exp/Cntr(USF)=0,0
Exp/Cntr=0.3,0.1

Type RM Length L Ch R = 1 ,7403    ,221.3,215.9,201.3
XS GIS Cut Line= 6
2204029.05836599683840.8490207062203824.37617029684067.943401045
2203717.20680878684080.8553723122203664.72713477684079.187621485
2203609.19369122684072.6368698482203547.06390207684162.433659297
#Sta/Elev= 30
       0 1785.32      15 1780.23    40.5 1773.76      67 1765.78      85 1762.83
      92 1760.33   102.8 1758.23   119.8 1756.14   156.6 1756.17   162.6 1757.62
   173.6 1755.21   190.6 1754.69   234.3 1750.27   285.8 1748.26   326.1 1747.96
   366.3 1745.52   375.4 1743.51   382.5 1742.14   386.5 1743.32   410.7 1744.07
     503 1740.82   522.8 1742.31   532.5 1740.32   556.8 1740.01   561.7 1741.22
   566.3  1744.9   571.4 1746.61   594.2 1749.18     620 1755.46   631.3 1759.24
#Mann= 9 ,-1,0
       0     .06       0      90      .1       0     110     .06       0
     230      .1       0     240     .07       0  358.57     .06       0
   375.4    .045       0   386.5     .06       0  453.67      .1       0
#XS Ineff= 2 , 0
                          408.56          1748.1
Permanent Ineff=
       F       F
Bank Sta=375.4,386.5
XS Rating Curve= 0 ,0
Exp/Cntr(USF)=0,0
Exp/Cntr=0.3,0.1

Type RM Length L Ch R = 1 ,7187    ,172.3,176.3,176.4
XS GIS Cut Line= 4
 2203806.5302004683718.3628078312203649.57097833683861.561285679
2203585.53878828683969.4302247172203523.64555288684165.091278002
#Sta/Elev= 30
       0 1766.51    29.1 1756.52      49 1750.92      79 1745.62   153.7 1734.53
   216.1 1733.06   239.9 1731.23   272.5  1731.6   291.1 1729.87   305.4 1729.97
   309.7 1730.88     319 1729.18   323.7 1730.93   328.3 1734.67     333 1736.62
   337.6 1735.25   345.2 1730.92   350.2 1730.34   375.4 1731.43   389.8 1736.45
   404.8 1738.75   417.4 1736.99   425.7 1738.28   438.3 1737.18   463.5 1737.58
   471.9 1742.72   475.8  1744.1     518 1755.46   526.4  1756.9   543.1 1762.75
#Mann= 5 ,-1,0
       0      .1       0  282.47     .06       0   291.1    .045       0
   305.4     .06       0  387.91      .1       0
Bank Sta=291.1,305.4
XS Rating Curve= 0 ,0
Exp/Cntr(USF)=0,0
Exp/Cntr=0.3,0.1

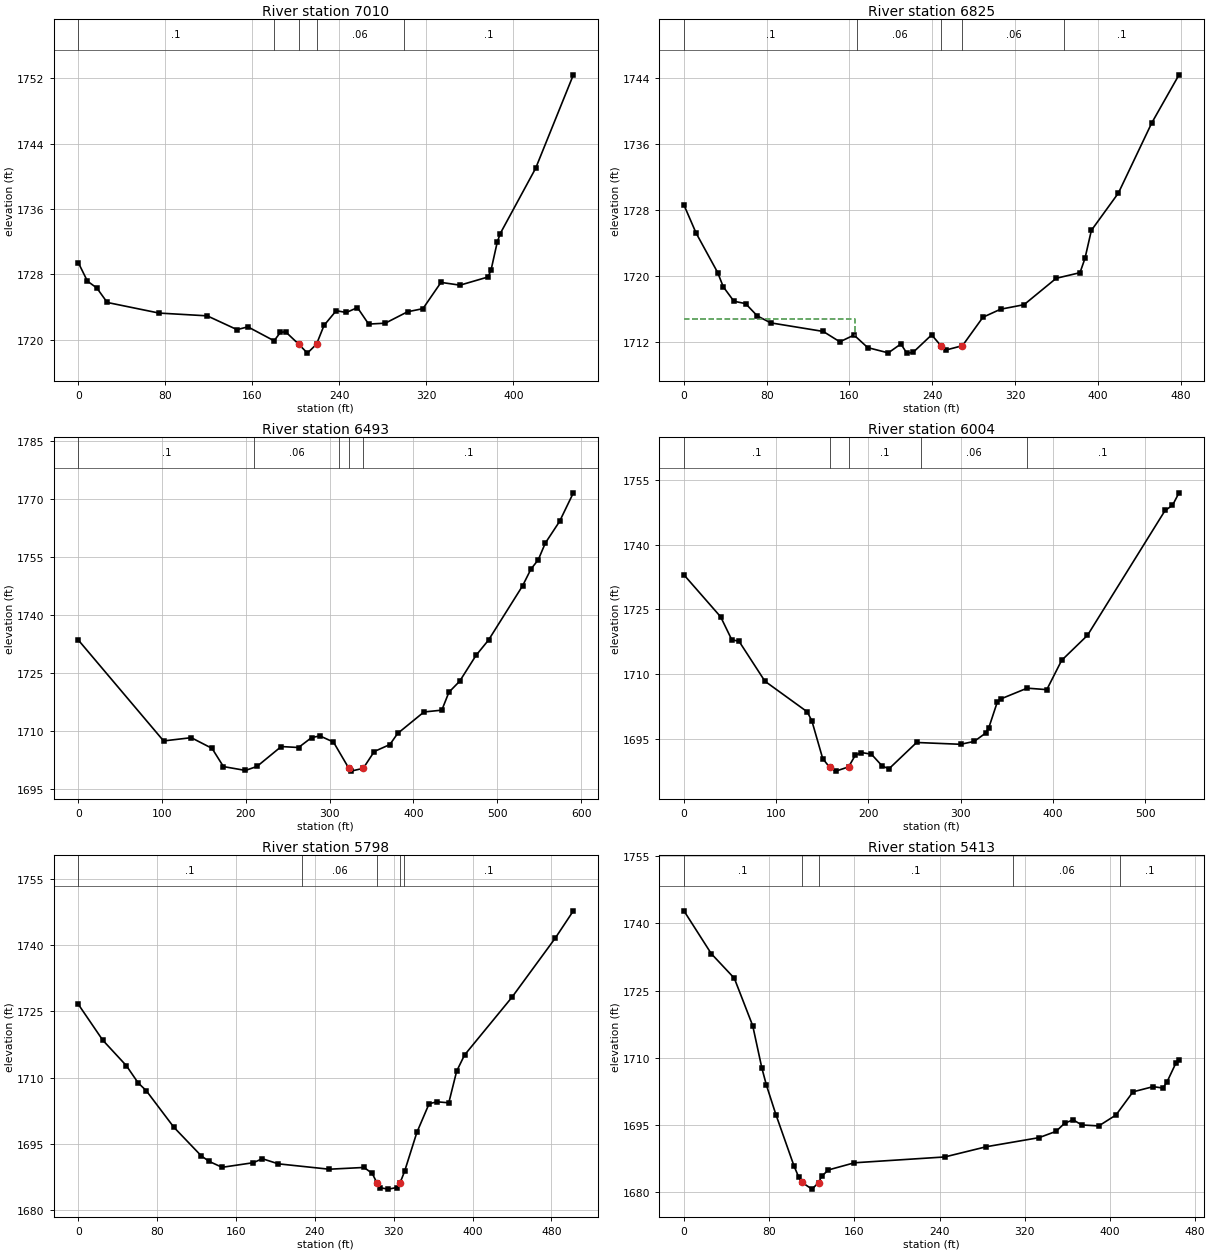
Type RM Length L Ch R = 1 ,7010    ,183.1,185.1,185.7
XS GIS Cut Line= 3
2203594.47688218683679.7401459742203470.46324882683847.910148779
2203316.90533277684040.241627357
#Sta/Elev= 30
       0 1729.42     8.4 1727.15      17 1726.32    26.6 1724.54    74.2 1723.24
   118.5  1722.9   145.9 1721.21   155.9 1721.55     180 1719.84   185.8 1720.88
   190.6 1720.94   202.9 1719.39   210.6 1718.33     219 1719.43   225.9 1721.73
   237.1 1723.53   246.4 1723.31   256.6 1723.91   266.9 1721.89   282.2    1722
   302.7  1723.4   316.8 1723.78   333.4    1727   350.9 1726.66   376.6 1727.66
   379.4  1728.5   385.1 1731.92   387.9 1732.99   420.4 1740.98   455.1 1752.44
#Mann= 5 ,-1,0
       0      .1       0     180     .06       0   202.9    .045       0
     219     .06       0  298.95      .1       0
Bank Sta=202.9,219
XS Rating Curve= 0 ,0
Exp/Cntr(USF)=0,0
Exp/Cntr=0.3,0.1

Type RM Length L Ch R = 1 ,6825    ,313.7,332.5,344.9
XS GIS Cut Line= 3
2203492.07168494683552.9080209532203386.84799603 683670.34517375
2203172.07025468683908.712016224
#Sta/Elev= 30
       0 1728.65    11.8 1725.23    32.6 1720.46      38 1718.73    48.3 1716.98
    59.6 1716.69    70.9  1715.2    83.8 1714.36   134.6 1713.32   150.7 1712.06
   164.4 1712.88   177.6 1711.36   197.5 1710.72   209.7  1711.8   215.4 1710.69
   221.4 1710.77   239.4  1712.9   248.8 1711.53     253 1711.06   269.2 1711.59
     289 1715.04     306 1716.01   328.7 1716.56   359.8 1719.76   382.8 1720.44
   387.6 1722.17   393.8 1725.57   419.9 1730.09   452.2  1738.6   478.5 1744.42
#Mann= 5 ,-1,0
       0      .1       0  167.68     .06       0   248.8    .045       0
   269.2     .06       0  367.68      .1       0
#XS Ineff= 2 , 0
          165.07  1714.8
Permanent Ineff=
       F       F
Bank Sta=248.8,269.2
XS Rating Curve= 0 ,0
Exp/Cntr(USF)=0,0
Exp/Cntr=0.3,0.1

Type RM Length L Ch R = 1 ,6493    ,499.8,488.9,470.2
XS GIS Cut Line= 4
2203478.82418036683481.2096952032203206.17132637 683550.79263078
2203102.99065468683490.352555545 2202924.6761269683555.431472671
#Sta/Elev= 30
       0 1733.51   101.8 1707.44   134.8 1708.28   159.6 1705.52   173.2 1700.81
   199.5 1699.82   213.3 1700.86   242.2 1705.99   262.8 1705.74   278.4  1708.3
   288.3 1708.74   304.5 1707.15  322.88 1700.36   325.4 1699.64     340 1700.36
   353.2 1704.71   371.8  1706.5   381.1 1709.37   412.5 1714.92   433.8 1715.39
   442.3 1720.03   455.1 1722.86   474.7 1729.56   489.6 1733.51   530.2 1747.51
   540.2 1751.84   548.9 1754.23   557.3 1758.54   574.3 1764.13   590.8 1771.53
#Mann= 5 ,-1,0
       0      .1       0     210     .06       0  311.39      .1       0
  322.88    .045       0     340      .1       0
Bank Sta=322.88,340
XS Rating Curve= 0 ,0
Exp/Cntr(USF)=0,0
Exp/Cntr=0.3,0.1

Type RM Length L Ch R = 1 ,6004    ,200.7,205.5,209
XS GIS Cut Line= 5
2203419.89711833683158.3618600942203321.77185288683163.581289108
2203236.17321707683212.6439218322203101.82857726683289.313162917
2202917.11605323683299.641018285
#Sta/Elev= 30
       0 1733.04    39.8 1723.29    51.8 1717.99    59.8 1717.59    87.8 1708.34
   133.7 1701.23   138.7 1699.11   150.4  1690.4   157.8 1688.38   164.7 1687.47
   178.5 1688.46   185.6 1691.11   192.3 1691.79   203.2  1691.4   214.9 1688.66
   222.2    1688   252.2 1694.12   299.9  1693.7   314.6 1694.37   327.1 1696.31
   330.5 1697.58   339.7 1703.54   343.3 1704.22     372 1706.73   393.3 1706.39
   409.4 1713.19   437.4    1719   521.5 1747.98   529.5 1749.16   536.6 1752.08
#Mann= 5 ,-1,0
       0      .1       0   157.8    .045       0   178.5      .1       0
  256.93     .06       0  371.61      .1       0
Bank Sta=157.8,178.5
XS Rating Curve= 0 ,0
Exp/Cntr(USF)=0,0
Exp/Cntr=0.3,0.1

Type RM Length L Ch R = 1 ,5798    ,373.9,385,392.7
XS GIS Cut Line= 5
2203397.01504163683148.7051414552203259.87110557 683146.37764099
2203133.20466744683078.9771509762203057.66963553683097.570389601
2202913.86516632683100.573347486
#Sta/Elev= 30
       0 1726.62    24.8 1718.48    48.8 1712.68    60.8 1708.76    68.9 1707.03
    96.9 1698.73   124.9 1692.19   132.9 1690.95   145.9 1689.62   177.6 1690.67
   186.7 1691.57   202.9 1690.41   254.6 1689.19   289.9 1689.59   298.2 1688.24
   303.2    1686   306.4 1684.97   314.7 1684.67   322.9 1685.03   326.3 1685.98
   331.1 1688.74   343.5 1697.53   355.9 1704.04   363.9 1704.49   375.9 1704.26
   383.9 1711.45   391.9 1715.11   439.9 1728.19     484 1741.66   502.3 1747.83
#Mann= 5 ,-1,0
       0      .1       0  227.16     .06       0   303.2    .045       0
   326.3     .06       0  330.65      .1       0
Bank Sta=303.2,326.3
XS Rating Curve= 0 ,0
Exp/Cntr(USF)=0,0
Exp/Cntr=0.3,0.1

Type RM Length L Ch R = 1 ,5413    ,193.3,188.2,181
XS GIS Cut Line= 3
2203476.01750458683049.9252156252203309.84043438682982.524725611
2203025.13146794682960.445254744
#Sta/Elev= 30
       0 1742.82    25.7 1733.25    47.3 1727.78    64.6 1717.17    73.2 1707.71
    77.5 1703.88    86.4 1697.32   103.4 1685.86   107.7 1683.44     111 1682.19
   120.2 1680.71   126.4 1682.15   129.3 1683.56   135.6 1684.99   160.1 1686.59
   244.9 1687.89   284.1 1690.18   333.5  1692.2   349.5 1693.61   357.5 1695.42
   365.5 1696.17   373.6 1695.03   389.6 1694.82   405.7 1697.25   421.7 1702.42
   440.6 1703.58   449.8 1703.27   453.7 1704.67   461.8 1708.75   464.9 1709.55
#Mann= 5 ,-1,0
       0      .1       0     111    .045       0   126.4      .1       0
  309.33     .06       0  409.33      .1       0
Bank Sta=111,126.4
XS Rating Curve= 0 ,0
Exp/Cntr(USF)=0,0
Exp/Cntr=0.3,0.1

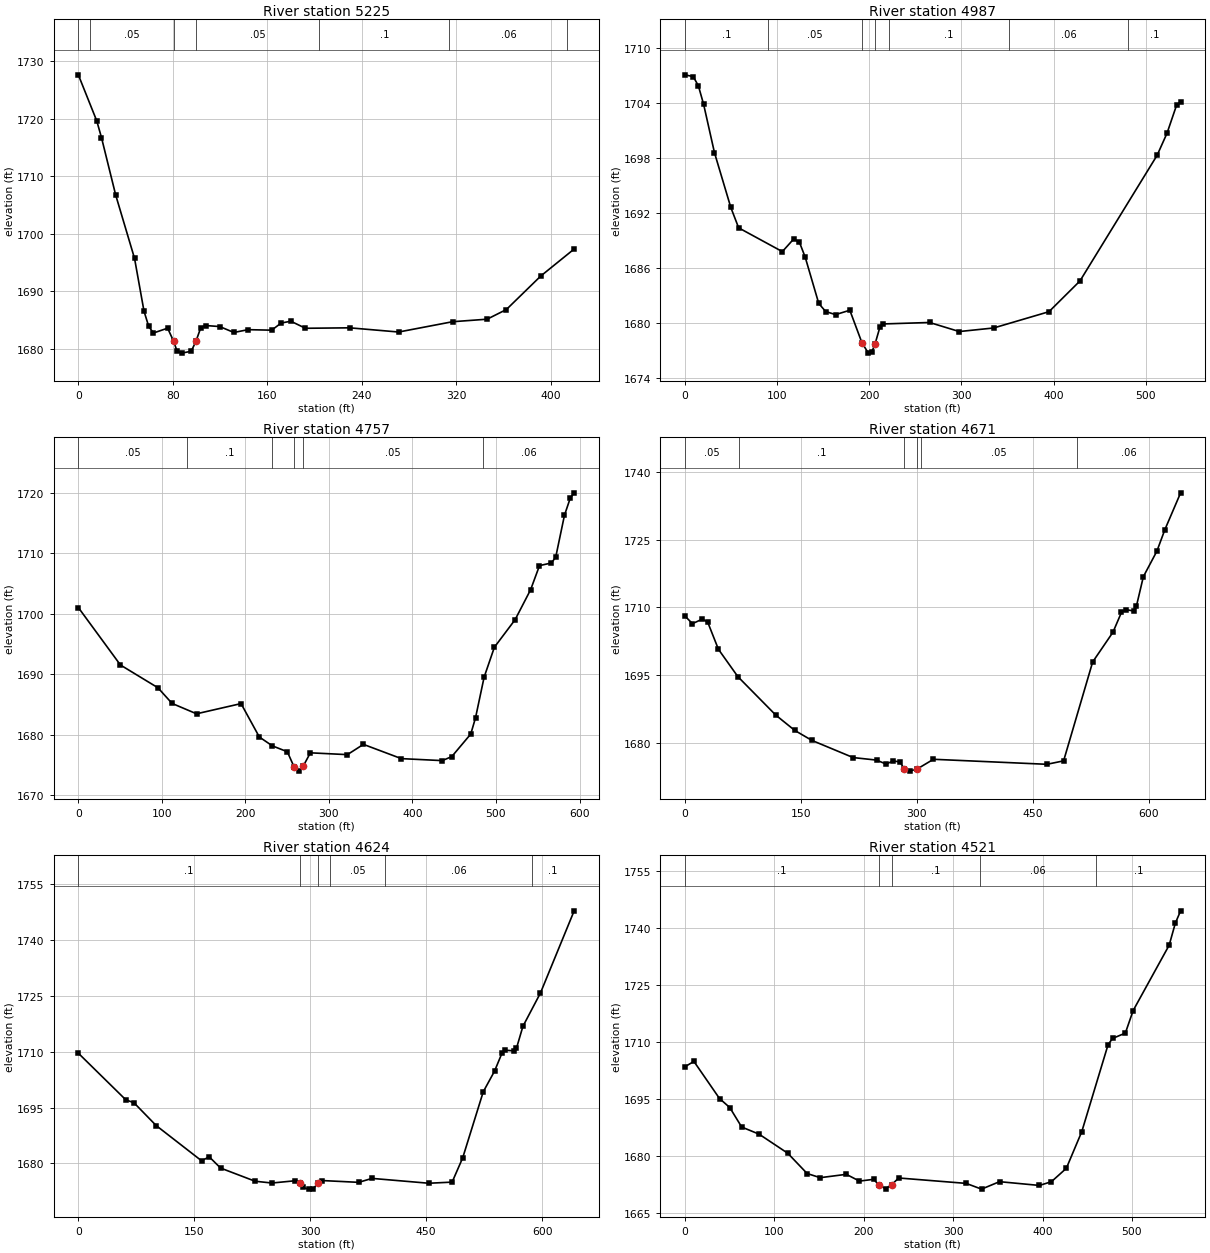
Type RM Length L Ch R = 1 ,5225    ,246.5,238.6,227.6
XS GIS Cut Line= 3
2203487.76153317682821.2217890892203313.79859049682827.385830365
 2203076.8254481  682892.4507105
#Sta/Elev= 30
       0 1727.62    15.6 1719.61    19.6 1716.71    31.6 1706.74    47.6 1695.69
    55.6 1686.53    59.6 1683.87    63.6 1682.73    75.6 1683.57    80.7 1681.29
    83.6 1679.56    87.6 1679.23    95.6 1679.56    99.6  1681.3   103.7 1683.67
   107.7 1684.03   119.7 1683.85   131.7 1682.82   143.7 1683.31   163.7 1683.22
   171.7 1684.46   179.9 1684.78   192.3 1683.55   229.7 1683.63   271.2  1682.9
   316.8 1684.69   346.1 1685.13   362.4 1686.81   391.6 1692.65   419.8 1697.33
#Mann= 7 ,-1,0
       0      .1       0      10     .05       0    80.7    .045       0
    99.6     .05       0  204.07      .1       0  314.07     .06       0
  414.07      .1       0
Bank Sta=80.7,99.6
XS Rating Curve= 0 ,0
Exp/Cntr(USF)=0,0
Exp/Cntr=0.3,0.1

Type RM Length L Ch R = 1 ,4987    ,232.1,229.4,225.7
XS GIS Cut Line= 3
2203444.82704091682497.0790127022203336.82610027682587.951204943
2203041.17315475682852.424183659
#Sta/Elev= 30
       0 1707.12     9.1 1706.93    14.7 1705.93    20.4  1703.9    32.2  1698.6
    49.9 1692.62    58.4 1690.39   105.8 1687.79   118.2 1689.18   124.4  1688.8
   130.6 1687.18   145.3 1682.12   152.8 1681.24   163.5  1680.9     179 1681.38
   192.11677.833   199.1 1676.69     203 1676.86   206.4 1677.71   211.8 1679.59
     215 1679.88   265.5 1680.04   297.7 1679.05     335 1679.44     395 1681.22
   428.6 1684.58   512.3 1698.32   523.1 1700.75   533.4  1703.8   537.8 1704.17
#Mann= 7 ,-1,0
       0      .1       0      90     .05       0   192.1    .045       0
   206.4     .05       0  221.15      .1       0  351.15     .06       0
  481.15      .1       0
Bank Sta=192.1,206.4
XS Rating Curve= 0 ,0
Exp/Cntr(USF)=0,0
Exp/Cntr=0.3,0.1

Type RM Length L Ch R = 1 ,4757    ,88.8,86.2,83.8
XS GIS Cut Line= 4
2203250.27888891682227.1526917062203187.21294765682408.820253842
2203103.43878687682535.8934190672202942.47944425682726.032525551
#Sta/Elev= 30
       0 1701.03    50.4 1691.52    95.3 1687.75   112.2 1685.16   141.5 1683.44
   194.8 1685.13   216.7  1679.6   232.3 1678.13   250.2 1677.16   258.3 1674.65
   264.1 1673.95   269.4 1674.82   277.8 1676.98   322.1 1676.68   341.3 1678.38
   386.7 1676.02   435.7 1675.69   447.1 1676.36   469.8 1680.09   475.5 1682.77
   485.8  1689.5   498.1 1694.46   522.9 1699.02   541.5 1703.99   552.1 1707.97
   566.3 1708.41   571.5 1709.36     582 1716.31     589 1719.17   593.6 1720.02
#Mann= 6 ,-1,0
       0     .05       0     130      .1       0   232.3     .05       0
   258.3    .045       0   269.4     .05       0  484.51     .06       0
Bank Sta=258.3,269.4
XS Rating Curve= 0 ,0
Exp/Cntr(USF)=0,0
Exp/Cntr=0.3,0.1

Type RM Length L Ch R = 1 ,4671    ,46.8,46.8,46.8
XS GIS Cut Line= 4
2203221.32868474 682181.13269094 2203107.7949617682341.146086804
2202993.82316466 682619.844509642202895.18574928682724.988391049
#Sta/Elev= 30
       0 1708.12     9.9  1706.4    22.7 1707.41    29.6 1706.75    43.5 1700.73
    68.7 1694.67   117.8 1686.16   142.3 1682.78   164.4 1680.58   217.8 1676.78
   248.1 1676.22   260.3 1675.35   269.7 1676.03   278.3 1675.82   283.7 1674.34
     291 1673.78   300.9 1674.28   321.7  1676.4   468.5 1675.29   490.1 1676.05
   527.7 1697.93     554 1704.52   564.9 1708.88   570.4 1709.51   581.6 1709.18
   584.3 1710.28   593.3  1716.8   610.8 1722.44   621.1 1727.19   641.5 1735.34
#Mann= 6 ,-1,0
       0     .05       0      70      .1       0   283.7    .045       0
   300.9      .1       0   306.2     .05       0   507.3     .06       0
Bank Sta=283.7,300.9
XS Rating Curve= 0 ,0
Exp/Cntr(USF)=0,0
Exp/Cntr=0.3,0.1

Type RM Length L Ch R = 1 ,4624    ,99.4,102.8,105.4
XS GIS Cut Line= 4
2203178.45650868682163.0713897422203064.92278564682323.084785606
 2202950.9509886682601.7832084422202852.31357322682706.927089851
#Sta/Elev= 30
       0 1709.61    61.4  1697.1      72  1696.3   100.7 1690.19   159.5 1680.72
   169.3  1681.8   184.1 1678.77   228.7 1675.24   250.5 1674.76   280.6 1675.37
   286.4 1674.68   290.4 1673.57   297.9 1673.12   303.9 1673.27     3101674.635
   314.9 1675.43   362.7 1674.94     380    1676   453.4  1674.7   483.6    1675
   497.3 1681.52   523.9 1699.26   538.5  1704.8   548.1 1709.62   552.6 1710.41
   563.9 1710.23   566.8 1710.89   575.2 1716.82   597.9 1725.78   641.5 1747.83
#Mann= 6 ,-1,0
       0      .1       0   286.4    .045       0     310      .1       0
   326.2     .05       0   396.2     .06       0   587.3      .1       0
Bank Sta=286.4,310
XS Rating Curve= 0 ,0
Exp/Cntr(USF)=0,0
Exp/Cntr=0.3,0.1

Type RM Length L Ch R = 1 ,4521    ,328.1,336.8,336.2
XS GIS Cut Line= 2
2203078.02415383682165.0280331522202760.81188212682619.667579844
#Sta/Elev= 30
       0 1703.56    10.2 1704.98    38.8 1695.23    50.3 1692.85    63.6 1687.73
    83.1 1685.85   115.1 1680.84   136.8  1675.5   151.4 1674.41   180.6 1675.29
   195.3 1673.51   211.2 1673.98   216.9 1672.51   224.5 1671.49   231.3 1672.57
   239.2 1674.33   314.6 1672.91   331.8  1671.4   351.9 1673.36   396.5 1672.37
   409.9 1673.35   426.6 1676.87   443.9 1686.53   473.3  1709.4   478.3 1711.03
   492.6 1712.43   501.3 1718.35   541.6 1735.55   548.5 1741.35   554.4 1744.58
#Mann= 5 ,-1,0
       0      .1       0   216.9    .045       0   231.3      .1       0
     330     .06       0     460      .1       0
Bank Sta=216.9,231.3
XS Rating Curve= 0 ,0
Exp/Cntr(USF)=0,0
Exp/Cntr=0.3,0.1