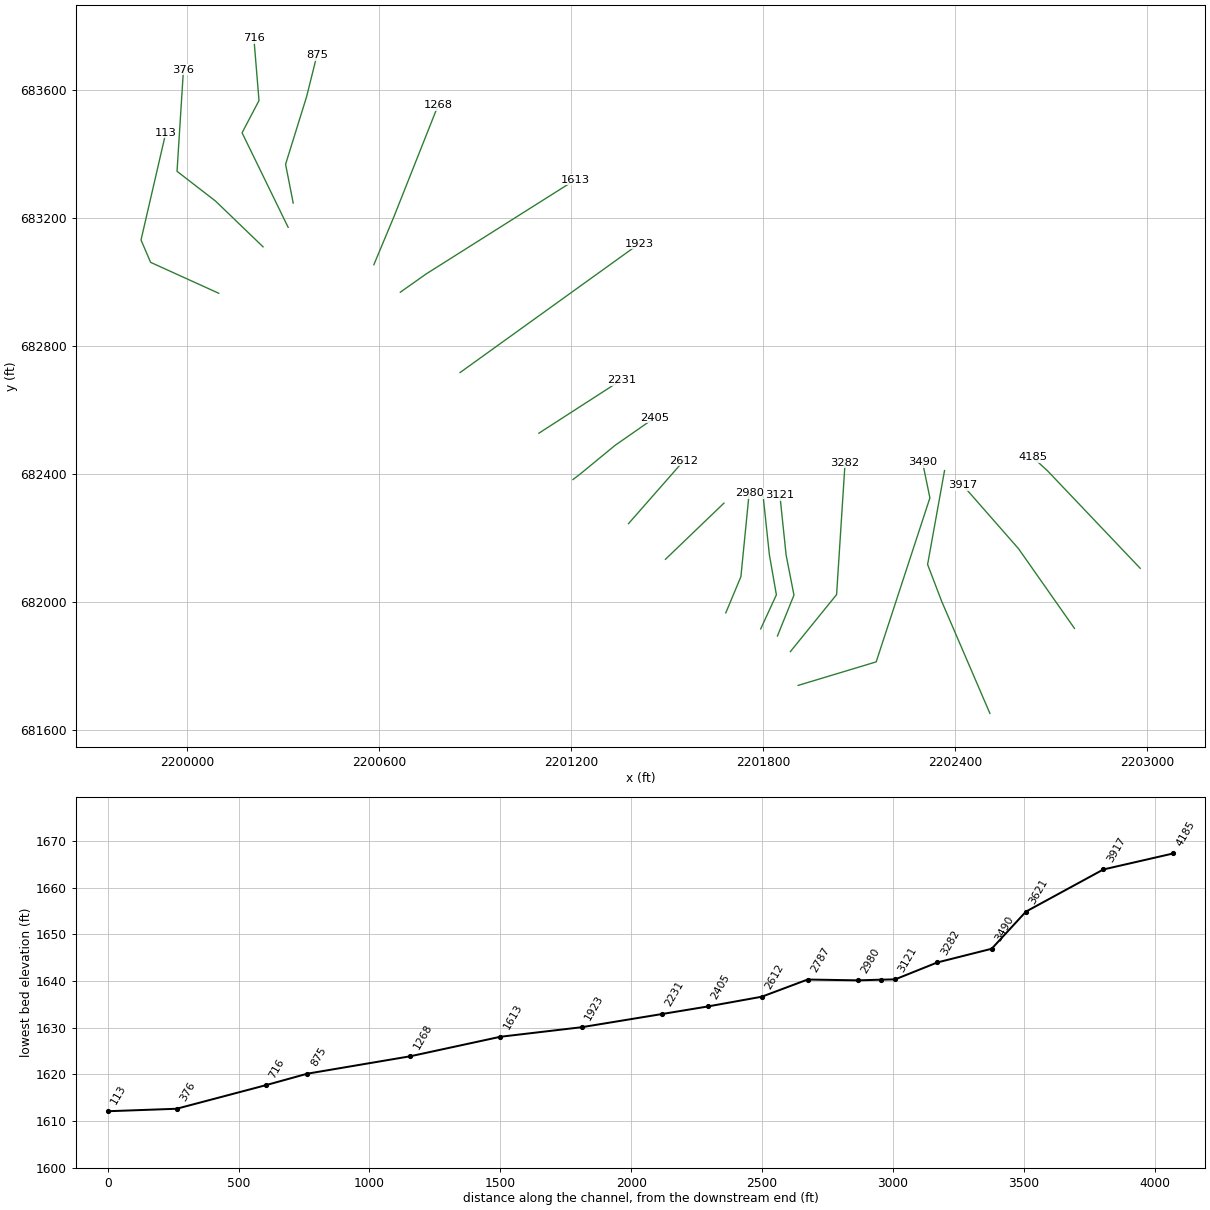
HEC-RAS study TENMILECK.prj: TENMILECK

--- TENMILECK.g01 (geometry) --- (continued)

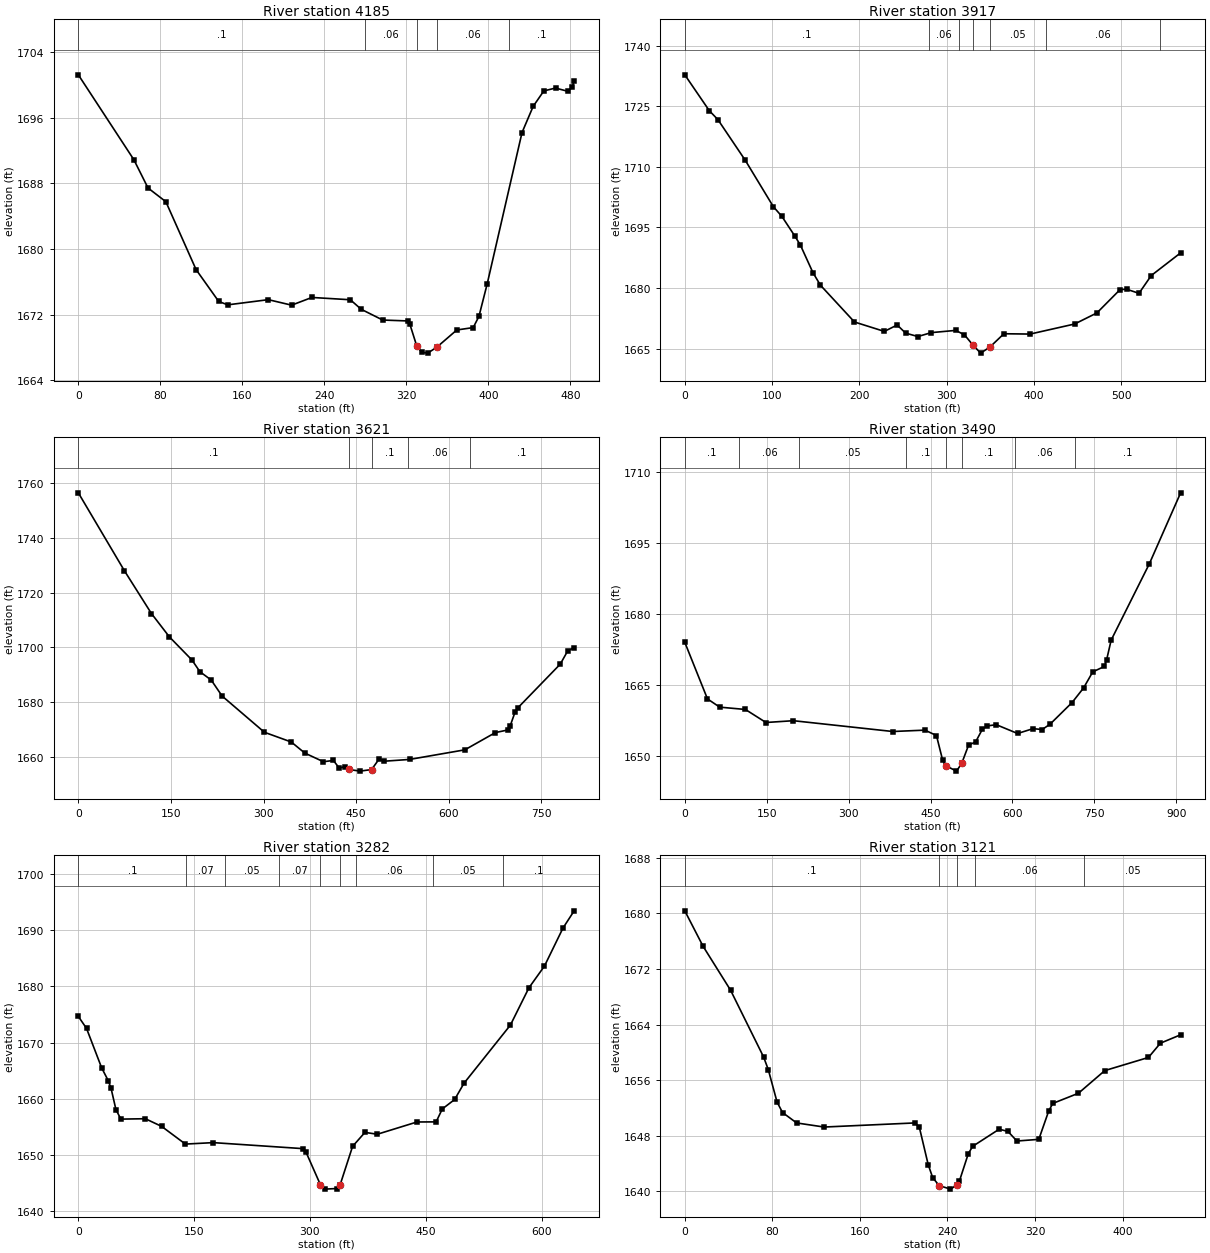
Type RM Length L Ch R = 1 ,4185    ,265.4,267.8,265
XS GIS Cut Line= 3
 2202979.0361109682105.8931261022202689.67096641682410.290226151
2202642.69610529 682453.50709838
#Sta/Elev= 30
       0  1701.2    54.2 1690.86      68 1687.42    85.4 1685.75   114.9 1677.48
     137  1673.6   145.8 1673.19   185.4 1673.82   208.1 1673.15   227.9 1674.09
   265.4 1673.81     276 1672.65     297 1671.34   321.2 1671.23   323.5 1670.83
   330.2 1668.18   335.1 1667.41   340.9 1667.31     3501668.054   369.3 1670.13
   385.3 1670.42   390.9 1671.79   398.9 1675.72   432.9 1694.16   443.8 1697.36
   454.2 1699.24   465.6 1699.59   477.4  1699.2   481.8 1699.66   483.8 1700.48
#Mann= 5 ,-1,0
       0      .1       0     280     .06       0   330.2    .045       0
     350     .06       0  419.99      .1       0
Bank Sta=330.2,350
XS Rating Curve= 0 ,0
Exp/Cntr(USF)=0,0
Exp/Cntr=0.3,0.1

Type RM Length L Ch R = 1 ,3917    ,297.6,295.7,286.8
XS GIS Cut Line= 3
2202773.52802472681918.1496855342202598.78154136682167.116449463
2202424.97455522682365.350363383
#Sta/Elev= 30
       0 1732.79    28.1  1723.9    37.9  1721.7    69.2 1711.64   101.4 1700.14
   111.2 1697.72   125.9  1692.9   132.4 1690.62   146.7 1683.82   155.3  1680.7
   194.3 1671.58   228.5 1669.25   243.2 1670.84   252.9 1668.82   266.9 1667.98
   282.3 1668.95   310.3  1669.5   320.3 1668.39   330.2 1665.81   338.8 1663.87
   349.5 1665.39   365.4 1668.67   395.4 1668.59   446.4 1671.08   471.9 1673.82
   498.4 1679.59   505.9  1679.7   520.1 1678.68   534.2 1683.09   567.8  1688.7
#Mann= 7 ,-1,0
       0      .1       0     280     .06       0  314.17     .05       0
   330.2    .045       0   349.5     .05       0  414.17     .06       0
  544.17      .1       0
Bank Sta=330.2,349.5
XS Rating Curve= 0 ,0
Exp/Cntr(USF)=0,0
Exp/Cntr=0.3,0.1

Type RM Length L Ch R = 1 ,3621    ,142.5,131.1,117.9
XS GIS Cut Line= 4
2202509.22212183681652.3797809342202358.86819964682001.773657262
2202314.47799404682117.7609686662202367.45985234682411.309102466
#Sta/Elev= 30
       0 1756.39    74.5    1728   118.4 1712.34   147.5 1703.82   184.1 1695.37
   196.8 1691.14   215.2 1688.08   232.8 1682.25   301.3 1669.03   344.9 1665.47
   366.7 1661.44   396.9 1658.28     413 1658.75   422.6 1655.93   431.1 1656.51
   437.8 1655.46   456.3 1654.85   474.9 1655.43   486.8 1659.19   495.4 1658.47
   536.5 1659.12   625.9 1662.62   675.3 1668.91     695 1669.85   699.1 1671.22
   707.2  1676.4   711.3 1677.84   780.4 1693.89   792.6 1698.77   802.9 1699.91
#Mann= 5 ,-1,0
       0      .1       0   437.8    .045       0   474.9      .1       0
  534.56     .06       0  634.56      .1       0
Bank Sta=437.8,474.9
XS Rating Curve= 0 ,0
Exp/Cntr(USF)=0,0
Exp/Cntr=0.3,0.1

Type RM Length L Ch R = 1 ,3490    ,205.2,207.6,213.7
XS GIS Cut Line= 4
2201909.85943627681739.8363117612202153.76258522681813.333500098
2202321.70641365682326.004134256 2202298.7246266682437.377409953
#Sta/Elev= 30
       0 1674.07    41.5 1662.13    63.9 1660.39     111  1659.9   148.6 1657.15
   198.8 1657.53   380.8 1655.25   439.8 1655.54   460.8  1654.4   472.1 1649.21
   478.5 1647.99   497.5 1646.89     507 1648.51   519.7  1652.4   532.4 1653.03
     545 1655.75   553.4 1656.42   570.3 1656.69   609.4 1654.83   637.6 1655.85
   654.4 1655.67   668.7 1656.78   709.2 1661.37   730.2 1664.44     747 1667.83
   768.1 1668.97   772.3 1670.33   780.7 1674.53   850.6 1690.63   907.9 1705.61
#Mann= 8 ,-1,0
       0      .1       0     100     .06       0     210     .05       0
  404.74      .1       0   478.5    .045       0     507      .1       0
  604.74     .06       0  714.74      .1       0
Bank Sta=478.5,507
XS Rating Curve= 0 ,0
Exp/Cntr(USF)=0,0
Exp/Cntr=0.3,0.1

Type RM Length L Ch R = 1 ,3282    ,157.4,161,165
XS GIS Cut Line= 3
2201885.50210087681845.3847651382202030.01450111 682023.70524308
2202056.53194771 682435.60958018
#Sta/Elev= 30
       0 1674.67    10.6 1672.55    30.2 1665.53    38.7 1663.26    42.4 1661.88
    48.7 1658.11    55.1 1656.41    86.8 1656.48   107.9 1655.12   138.7 1651.97
   174.8 1652.23   291.1 1651.16   295.1 1650.49   313.71644.711   319.2 1643.96
   335.2 1644.07   339.2 1644.76   355.3 1651.57   371.3 1654.05   387.3 1653.72
   438.7  1655.9   463.5 1655.92   471.5 1658.22   487.5  1659.9   499.6 1662.79
   559.7 1673.13   583.7 1679.76   603.8 1683.62   627.8 1690.38   642.3 1693.45
#Mann= 9 ,-1,0
       0      .1       0     140     .07       0     190     .05       0
  259.53     .07       0   313.7    .045       0   339.2     .07       0
  359.53     .06       0  459.53     .05       0  549.53      .1       0
Bank Sta=313.7,339.2
XS Rating Curve= 0 ,0
Exp/Cntr(USF)=0,0
Exp/Cntr=0.3,0.1

Type RM Length L Ch R = 1 ,3121    ,54.6,54.8,55.4
XS GIS Cut Line= 4
2201845.17099295681894.4068023032201896.74939046682022.084474823
2201872.22851295682147.2255048432201852.78092045682334.091502373
#Sta/Elev= 30
       0 1680.37    16.7 1675.27    41.8 1668.96      72 1659.35    76.3 1657.53
    84.3 1652.87    89.3 1651.36   102.2 1649.86   127.3 1649.27   210.1 1649.86
   214.2 1649.33   222.4 1643.88   226.5    1642   232.41640.851   242.8 1640.34
   248.61640.927   250.9 1641.48   259.1 1645.45   263.1  1646.5   287.3 1648.96
   295.3 1648.64   303.5 1647.26   323.5  1647.5   332.6  1651.6   336.3 1652.67
   359.7 1654.13   383.8 1657.39   423.7 1659.28   434.6 1661.33   453.1 1662.54
#Mann= 5 ,-1,0
       0      .1       0   232.4    .045       0   248.6      .1       0
  265.22     .06       0  365.22     .05       0
Bank Sta=232.4,248.6
XS Rating Curve= 0 ,0
Exp/Cntr(USF)=0,0
Exp/Cntr=0.3,0.1

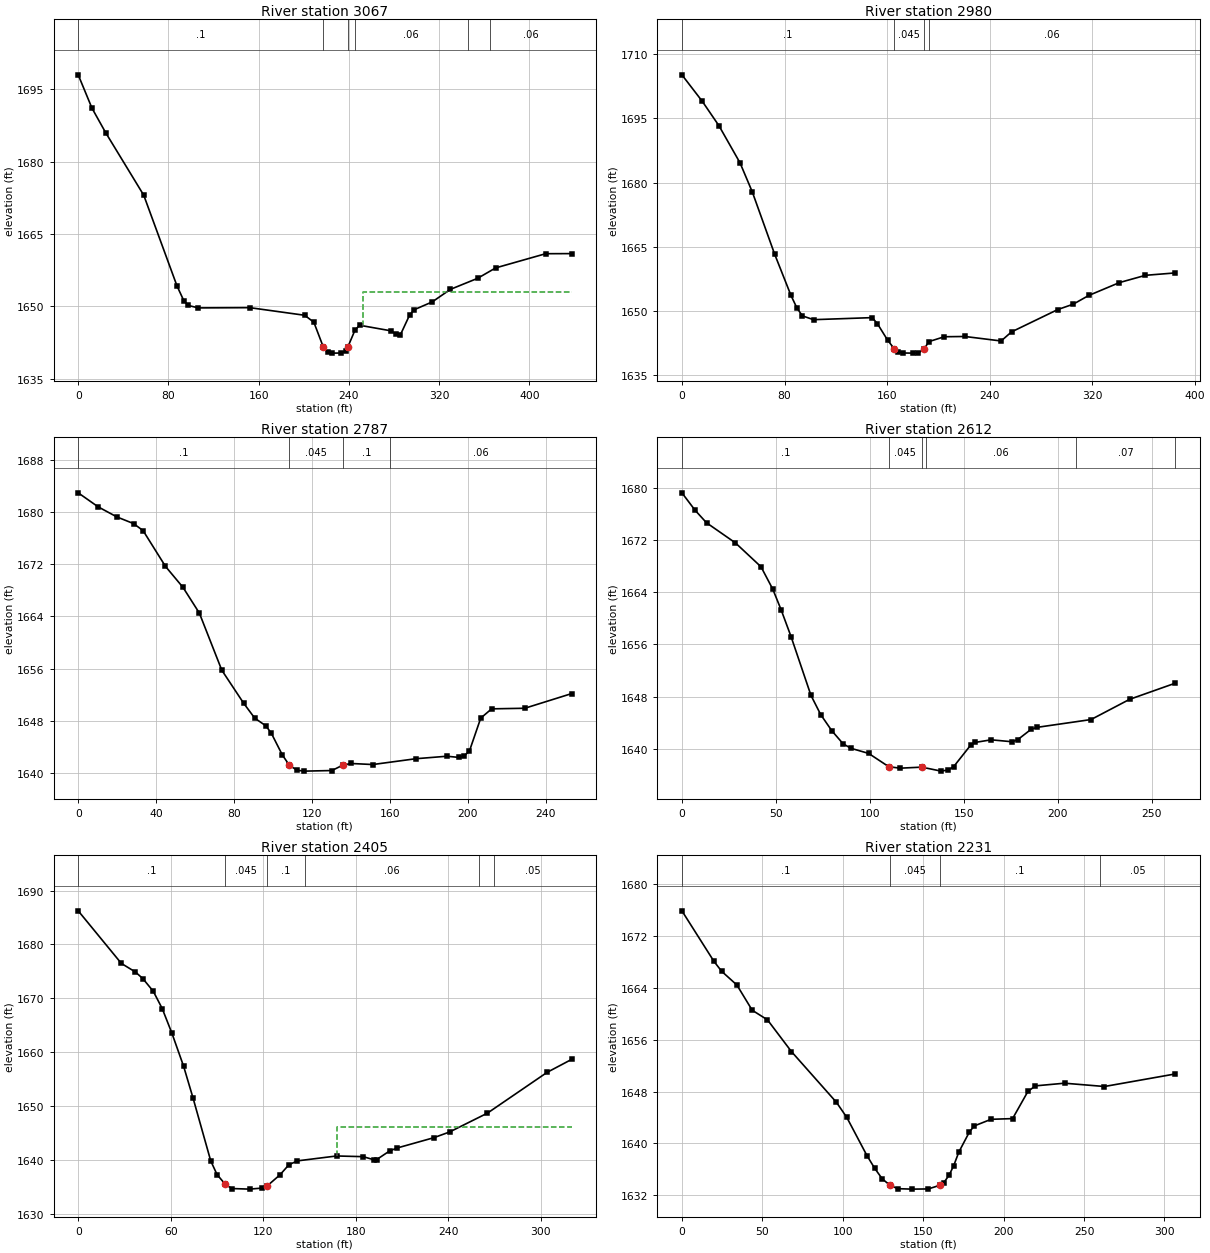
Type RM Length L Ch R = 1 ,3067    ,90.9,86.7,82.3
XS GIS Cut Line= 4
2201792.74704794681916.3910373072201841.78880295682022.930022324
2201819.80456794682148.9165998442201799.51142794682340.010334874
#Sta/Elev= 30
       0 1697.99    12.2 1691.08    24.3 1686.01    58.1 1673.02    87.6 1654.19
    93.6 1651.15    97.7 1650.15   106.5 1649.65   152.1  1649.7   200.8 1648.12
   208.9 1646.67   217.4 1641.46   221.1 1640.43   225.1 1640.27   233.3 1640.29
   237.3 1640.76     2391641.531   245.4 1645.06   249.5 1646.05   277.6 1644.88
   281.6 1644.18   285.7 1644.11   293.7 1648.13   297.7 1649.26   313.8 1650.89
   329.9 1653.49     354 1655.78   370.1 1657.95   414.4 1660.89   437.3 1660.91
#Mann= 6 ,-1,0
       0      .1       0   217.4    .045       0     239      .1       0
  245.17     .06       0  345.17     .05       0  365.17     .06       0
#XS Ineff= 2 , 0
                          252.11         1653.02
Permanent Ineff=
       F       F
Bank Sta=217.4,239
XS Rating Curve= 0 ,0
Exp/Cntr(USF)=0,0
Exp/Cntr=0.3,0.1

Type RM Length L Ch R = 1 ,2980    ,203.9,193.2,179
XS GIS Cut Line= 3
2201683.61258192681966.5143397862201730.86667175682079.637766958
2201756.64162984682340.251232087
#Sta/Elev= 30
       0 1705.19    15.9 1698.99    28.9 1693.28    45.3 1684.61    54.9 1677.79
    72.2 1663.33      85 1653.63    89.6 1650.71    93.9 1648.84   102.6 1647.95
   148.3 1648.43   152.3 1647.05   160.3 1643.18   165.4 1641.19   168.4 1640.46
   172.4 1640.16   180.1 1640.13   184.4 1640.19   188.5 1640.98   192.5 1642.82
   204.5 1643.96   220.6 1644.02   248.8 1642.97   256.9 1645.09     293 1650.32
     305 1651.57   317.1 1653.61     341 1656.62   361.3 1658.32   384.5 1658.88
#Mann= 4 ,-1,0
       0      .1       0   165.4    .045       0   188.5      .1       0
   192.6     .06       0
Bank Sta=165.4,188.5
XS Rating Curve= 0 ,0
Exp/Cntr(USF)=0,0
Exp/Cntr=0.3,0.1

Type RM Length L Ch R = 1 ,2787    ,173.5,175.2,176.9
XS GIS Cut Line= 2
 2201495.1231773682134.1288922432201677.80319276682309.501707086
#Sta/Elev= 30
       0 1682.93    10.2 1680.79    19.9 1679.23    28.4 1678.22    33.3 1677.14
    44.8 1671.66    53.8 1668.44    62.2  1664.5    73.7 1655.76    84.9 1650.71
    90.6 1648.42    96.3 1647.24    99.1 1646.12   104.7 1642.82   108.4 1641.18
   112.4 1640.43   116.1  1640.3   130.2 1640.39   135.9 1641.23   140.1 1641.47
   151.2 1641.31   173.3  1642.2   189.2 1642.58   195.5  1642.4   198.1 1642.63
   200.8 1643.38   206.6 1648.42   212.2 1649.84   229.2 1649.93   253.2 1652.17
#Mann= 4 ,-1,0
       0      .1       0   108.4    .045       0   135.9      .1       0
     160     .06       0
Bank Sta=108.4,135.9
XS Rating Curve= 0 ,0
Exp/Cntr(USF)=0,0
Exp/Cntr=0.3,0.1

Type RM Length L Ch R = 1 ,2612    ,211,206.7,203.3
XS GIS Cut Line= 2
2201379.54683328 682245.529693052201552.83187652682442.824109747
#Sta/Elev= 30
       0 1679.19       7 1676.53    13.1 1674.61    28.5 1671.53    42.1 1667.88
    48.4 1664.44    52.8 1661.31    58.1  1657.2    68.7 1648.21    73.9 1645.26
    79.8  1642.8    85.8  1640.8      90 1640.11    99.4 1639.33   110.1  1637.3
   116.1 1637.07   127.7 1637.23     138 1636.62   141.9 1636.81   144.7 1637.32
   153.9 1640.66   156.1 1641.01   164.6 1641.41   175.9 1641.11   178.8 1641.44
   185.9 1643.02   188.9 1643.31   217.8 1644.51   238.3  1647.6   262.6 1650.07
#Mann= 6 ,-1,0
       0      .1       0   110.1    .045       0   127.7      .1       0
     130     .06       0     210     .07       0  262.59     .05       0
Bank Sta=110.1,127.7
XS Rating Curve= 0 ,0
Exp/Cntr(USF)=0,0
Exp/Cntr=0.3,0.1

Type RM Length L Ch R = 1 ,2405    ,174.9,173.8,171.5
XS GIS Cut Line= 4
2201205.98378113682383.3087552842201227.75391477682399.992146179
2201337.75221176682490.3478901322201461.08161737682576.218268619
#Sta/Elev= 30
       0 1686.23      28 1676.46    37.1 1674.87    41.9 1673.65    48.7 1671.29
    54.5 1668.08    60.8  1663.5    68.4 1657.35    74.6 1651.37      86 1639.77
    90.1 1637.23    95.3 1635.47    99.6 1634.64   111.2 1634.53   119.5 1634.73
   122.4 1635.07   130.9 1637.18   136.7 1639.05   142.2 1639.78   167.7 1640.69
     185 1640.56   192.2 1639.95   193.7 1640.03     202 1641.61   206.8 1642.16
   230.7 1644.08     241 1645.15   265.5 1648.64   304.3 1656.23   320.1 1658.62
#Mann= 6 ,-1,0
       0      .1       0    95.3    .045       0   122.4      .1       0
  147.43     .06       0  259.78     .07       0  269.78     .05       0
#XS Ineff= 2 , 0
                          167.61         1646.13
Permanent Ineff=
       F       F
Bank Sta=95.3,122.4
XS Rating Curve= 0 ,0
Exp/Cntr(USF)=0,0
Exp/Cntr=0.3,0.1

Type RM Length L Ch R = 1 ,2231    ,306.3,308,308.6
XS GIS Cut Line= 2
2201099.43668072 682528.248207732201357.18626161682694.496687409
#Sta/Elev= 30
       0 1675.93    19.9 1668.13    24.7 1666.59    34.2 1664.46    43.7 1660.57
    53.2 1659.08    68.1 1654.18    96.1 1646.33   102.5 1644.01   115.1 1638.08
   119.9 1636.12   124.6  1634.5   129.4 1633.51   134.2 1632.99     143 1632.92
   153.2 1632.95   160.3 1633.51   162.7 1633.88   166.1 1635.06     169 1636.56
   172.2 1638.66   178.8 1641.78   181.8 1642.69   192.2 1643.71   205.6 1643.82
   215.1 1648.01   219.8 1648.88   237.9 1649.29   262.7 1648.78   306.7 1650.72
#Mann= 4 ,-1,0
       0      .1       0   129.4    .045       0   160.3      .1       0
     260     .05       0
Bank Sta=129.4,160.3
XS Rating Curve= 0 ,0
Exp/Cntr(USF)=0,0
Exp/Cntr=0.3,0.1

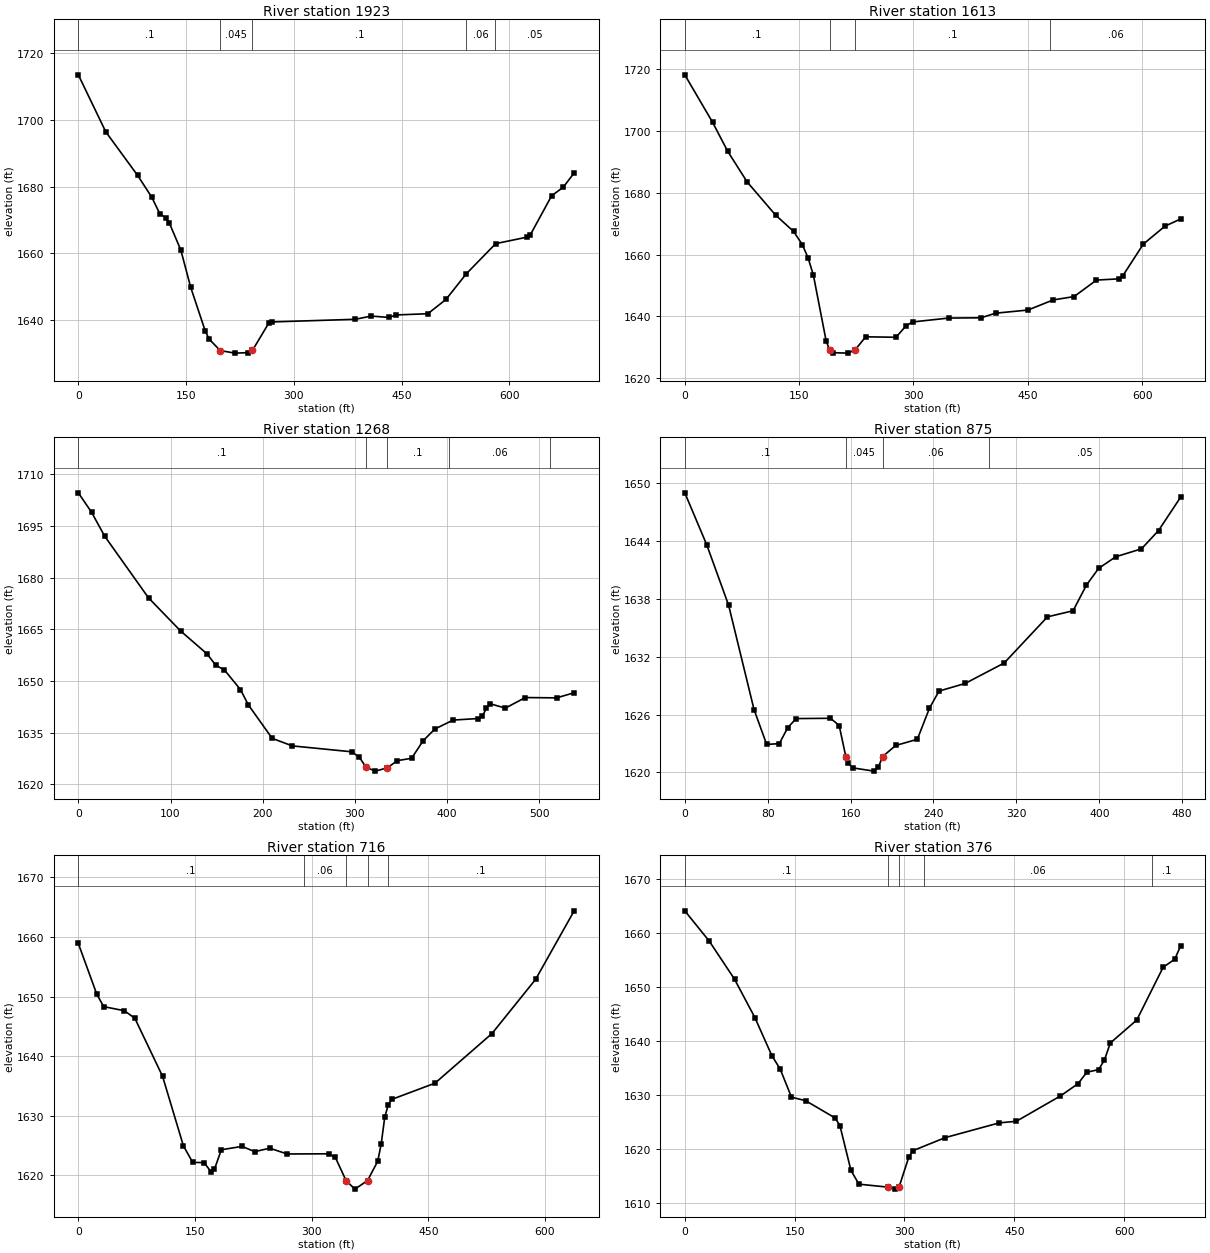
Type RM Length L Ch R = 1 ,1923    ,310.4,309.8,308.7
XS GIS Cut Line= 2
2200853.14617241682717.8691648372201413.54821043683120.934353072
#Sta/Elev= 30
       0 1713.58    38.2 1696.48    82.6 1683.39   102.3 1676.84   113.4 1671.92
   122.1 1670.63   126.9 1669.01   142.7    1661   156.4 1649.87   176.9 1636.59
   182.2 1634.28   197.5 1630.86     218 1630.09   236.7 1630.23   242.4 1630.91
   264.9 1639.01   269.8 1639.45   385.7 1640.24   407.8 1641.21   432.4  1640.8
   442.2 1641.54   486.6 1641.91   511.8 1646.19     540 1653.86   581.1 1662.94
   624.6 1664.88   629.5 1665.67     659 1677.31   675.2 1679.88   690.3 1684.15
#Mann= 5 ,-1,0
       0      .1       0   197.5    .045       0   242.4      .1       0
     540     .06       0     580     .05       0
Bank Sta=197.5,242.4
XS Rating Curve= 0 ,0
Exp/Cntr(USF)=0,0
Exp/Cntr=0.3,0.1

Type RM Length L Ch R = 1 ,1613    ,329.9,344.8,366.8
XS GIS Cut Line= 3
2200666.28521818682969.0117585142200747.42860476683026.289443158
2201213.60531589683320.633100356
#Sta/Elev= 30
       0 1718.22    36.6 1702.78    56.2 1693.48    81.8 1683.52   119.1 1672.78
   142.8 1667.47   154.2 1663.21   161.7 1658.96   168.7 1653.35   185.4 1632.09
   190.1 1628.92   194.8 1628.19   213.7 1628.05   223.2 1629.04   237.4 1633.34
   277.1 1633.19   290.4 1636.92   298.9 1638.15   346.2 1639.41   388.8  1639.5
   407.7 1640.99   450.3 1642.01   483.4 1645.29   510.8 1646.37   540.2 1651.72
   569.3 1652.11   574.6 1653.06   601.6 1663.36     630 1669.18   650.6 1671.52
#Mann= 4 ,-1,0
       0      .1       0   190.1    .045       0   223.2      .1       0
  479.32     .06       0
Bank Sta=190.1,223.2
XS Rating Curve= 0 ,0
Exp/Cntr(USF)=0,0
Exp/Cntr=0.3,0.1

Type RM Length L Ch R = 1 ,1268    ,390,393.3,395.6
XS GIS Cut Line= 3
 2200583.5507848 683054.928285482200645.97355195683204.242863337
2200784.57243005683553.641066956
#Sta/Elev= 30
       0 1704.59    14.4 1698.93    28.5 1692.04    76.1 1674.13   110.8 1664.55
   139.8 1657.82   148.9 1654.61   158.5 1653.19   175.8 1647.53   184.4 1643.08
   210.2 1633.38     232 1631.19   296.7 1629.47   304.9 1627.84   312.1 1624.97
   322.1 1623.87     335 1624.81     346 1626.92   361.4 1627.59   373.9 1632.67
   386.6 1636.08   406.5 1638.68   433.9 1639.13   438.3 1639.88   442.6 1642.14
   446.9 1643.38   463.1 1642.15   484.7 1645.21   518.6 1645.12   537.7  1646.6
#Mann= 5 ,-1,0
       0      .1       0   312.1    .045       0     335      .1       0
  401.84     .06       0  511.84     .05       0
Bank Sta=312.1,335
XS Rating Curve= 0 ,0
Exp/Cntr(USF)=0,0
Exp/Cntr=0.3,0.1

Type RM Length L Ch R = 1 ,875     ,160.1,159,152.3
XS GIS Cut Line= 4
2200331.40526009 683247.658683752200307.56342385683368.800986774
2200373.28956698683580.1556431132200405.58938834683709.883215004
#Sta/Elev= 30
       0    1649    21.1 1643.63    42.3 1637.34    66.8 1626.53      79 1622.91
    91.2 1622.99    99.4 1624.66   107.5 1625.59   140.6 1625.62     149 1624.87
   155.41621.637   157.4 1620.95   162.6 1620.47   182.5 1620.14   186.7 1620.52
   190.9 1621.65   203.5  1622.8   224.4 1623.44   236.1 1626.66   245.3 1628.44
   270.5 1629.23   308.2 1631.35     350 1636.14   374.7 1636.77   387.6 1639.43
   399.4 1641.17   415.9 1642.37   440.7 1643.19   457.2 1645.09   478.5 1648.55
#Mann= 4 ,-1,0
       0      .1       0   155.4    .045       0   190.9     .06       0
  293.47     .05       0
Bank Sta=155.4,190.9
XS Rating Curve= 0 ,0
Exp/Cntr(USF)=0,0
Exp/Cntr=0.3,0.1

Type RM Length L Ch R = 1 ,716     ,301.6,340.5,372.4
XS GIS Cut Line= 4
 2200315.5466756683171.8748938682200171.57455089683467.202329175
2200224.48738305683568.105869571 2200208.4904803683762.529764481
#Sta/Elev= 30
       0  1658.9    23.7 1650.39    32.6  1648.3    59.3 1647.61    72.7 1646.34
   108.3 1636.61   135.1 1624.94   147.1 1622.16   161.7 1622.12   170.6 1620.59
     175    1621   183.9 1624.28   210.6 1624.84   226.8 1623.96   246.2 1624.54
   268.5 1623.57   321.9  1623.6   330.5 1622.99   344.3  1619.1   355.7 1617.67
   371.9 1619.11     385 1622.35   389.5 1625.28     394 1629.72   398.6 1631.85
     403 1632.73   458.6 1635.45   531.9 1643.78   588.1 1652.89   637.6 1664.38
#Mann= 5 ,-1,0
       0      .1       0     290     .06       0   344.3    .045       0
   371.9     .06       0  398.55      .1       0
Bank Sta=344.3,371.9
XS Rating Curve= 0 ,0
Exp/Cntr(USF)=0,0
Exp/Cntr=0.3,0.1

Type RM Length L Ch R = 1 ,376     ,274.6,263,227.5
XS GIS Cut Line= 4
2200237.11235686683110.7987380972200088.40764139683253.974668301
2199968.23711532683346.8220330182199988.38401129683664.960337027
#Sta/Elev= 30
       0 1664.18    33.5 1658.55    67.9 1651.52    95.7 1644.41   118.8 1637.38
   130.3 1634.85   145.7 1629.66   164.9 1629.02   205.3 1625.81   211.8 1624.41
   226.9 1616.09   237.8 1613.55   277.3    1613   287.6 1612.63   292.7 1613.06
   305.8 1618.53   311.5 1619.75   355.6 1622.17   429.3  1624.9   452.8  1625.2
     513 1629.89     537 1632.16     549 1634.28   565.1 1634.77   573.1 1636.56
   581.1  1639.7   617.2 1643.95   653.2 1653.72     669 1655.21   677.1 1657.67
#Mann= 5 ,-1,0
       0      .1       0   277.3    .045       0   292.7      .1       0
  326.43     .06       0  638.29      .1       0
Bank Sta=277.3,292.7
XS Rating Curve= 0 ,0
Exp/Cntr(USF)=0,0
Exp/Cntr=0.3,0.1

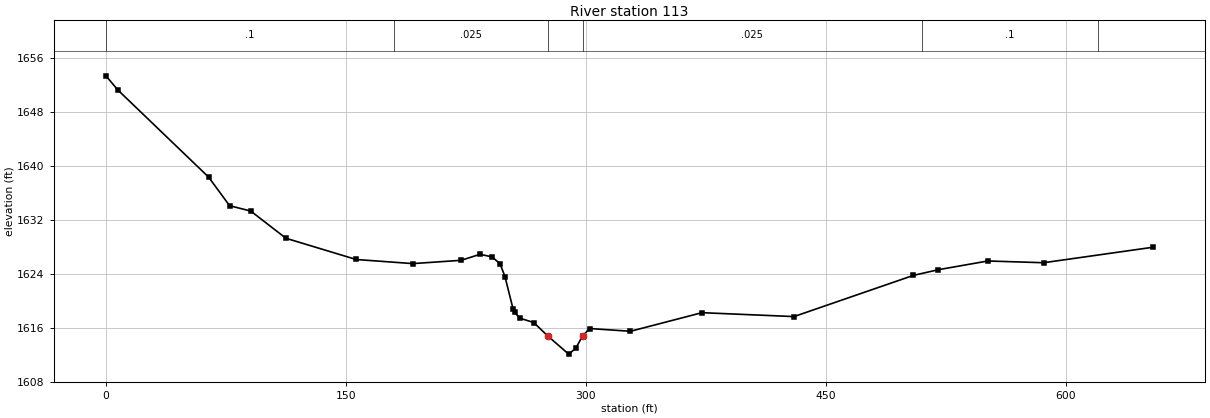
Type RM Length L Ch R = 1 ,113     ,,,
XS GIS Cut Line= 4
2200098.59385736682965.6421756572199885.66750448683062.293893074
2199855.68025867683132.1722716532199933.22486392683467.811786565
#Sta/Elev= 30
       0 1653.39     7.5 1651.28    64.2 1638.36    77.3 1634.12    90.5 1633.33
   112.5 1629.29   156.4 1626.14   191.8 1625.53     222 1626.02   233.8 1626.91
   241.3 1626.53   246.3 1625.51   249.4  1623.6   254.4 1618.85   255.4 1618.34
   258.5 1617.45   267.4 1616.78   276.2 1614.78   289.2  1612.1   293.6 1612.96
   297.9  1614.8   302.3  1615.9   327.8 1615.49   372.5 1618.25     430 1617.67
   504.6 1623.78   520.3 1624.63   551.2 1625.92     586 1625.66   654.4 1627.96
#Mann= 6 ,-1,0
       0      .1       0     180    .025       0   276.2    .045       0
   297.9    .025       0  509.88      .1       0  619.88     .06       0
Bank Sta=276.2,297.9
XS Rating Curve= 0 ,0
Exp/Cntr(USF)=0,0
Exp/Cntr=0.3,0.1
LCMann Table=0

Chan Stop Cuts=-1
Use User Specified Reach Order=0
Composite Channel Slope=5